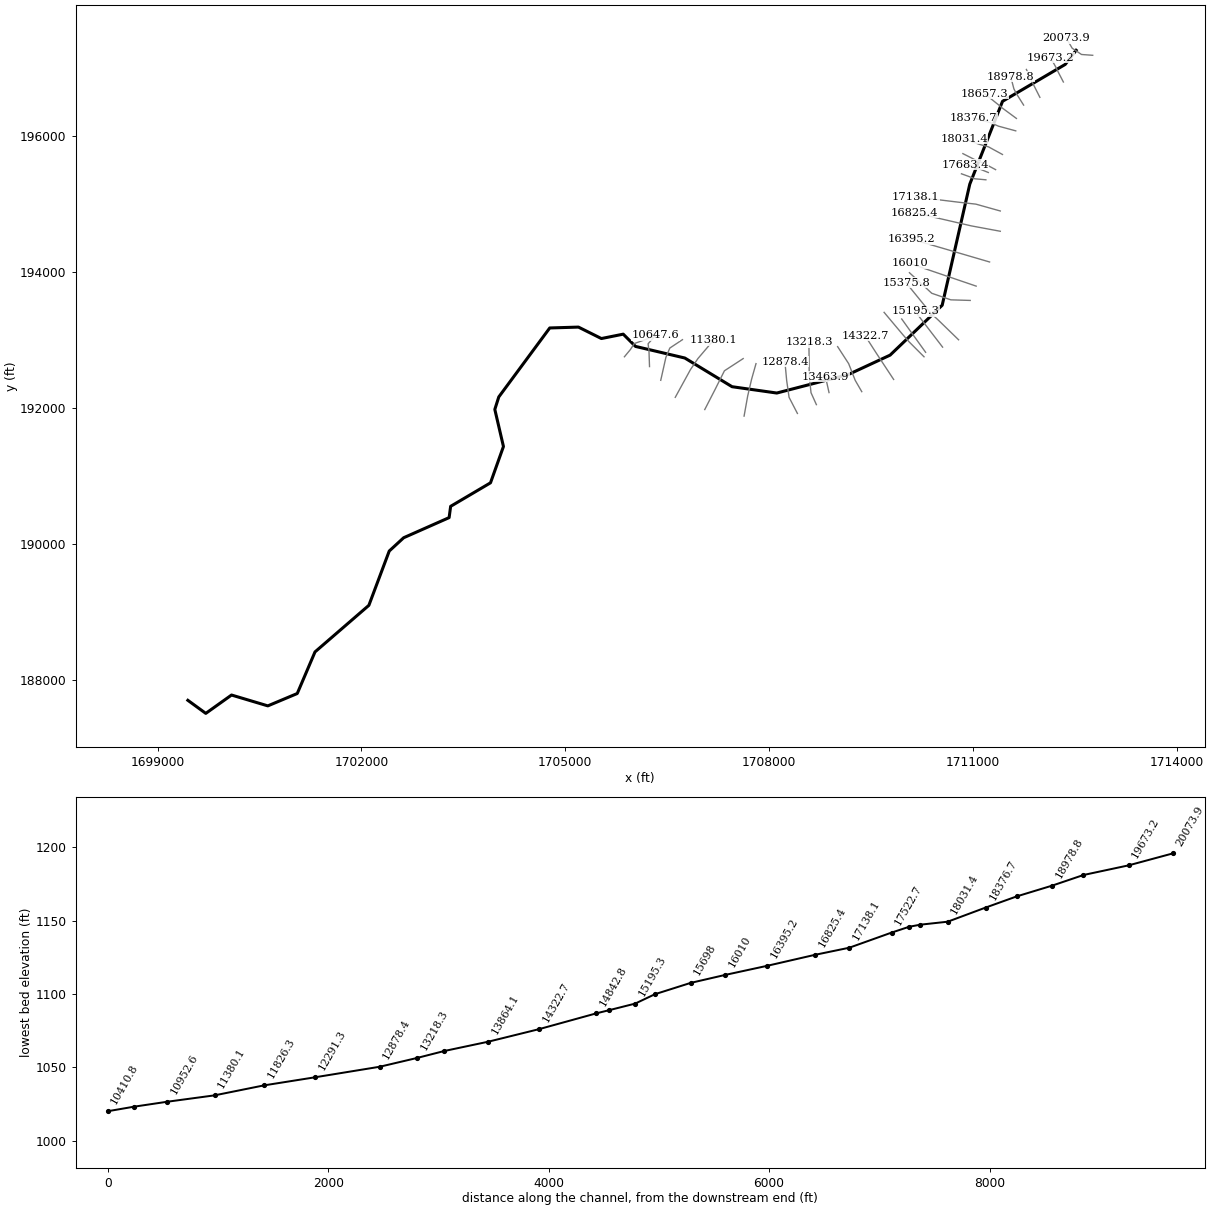
--- Sims Fork.prj (project) ---

Proj Title=Sims Fork
Current Plan=p01
Default Exp/Contr=0,0
English Units
Geom File=g01
Flow File=f01
Plan File=p01
BEGIN DESCRIPTION:
END DESCRIPTION:
DSS Export Rating Curves= 0
DSS Export Rating Curve Sorted= 0
DSS Export Volume Flow Curves= 0
DXF OffsetX= 0
DXF OffsetY= 0
DXF ScaleX= 0
DXF ScaleY= 0

--- Sims Fork.p01 (plan) ---

Plan Title=Floodplain
Program Version=4.00
Geom File=g01
Flow File=f01
K Sum by GR=0
Std Step Tol=0.01
Critical Tol=0.01
Num of Std Step Trials=20
Max Error Tol=0.3
Flow Tol Ratio=0.001
Split Flow NTrial=30
Split Flow Tol=0.02
Split Flow Ratio=0.02
Log Output Level=0
Friction Slope Method=1
Unsteady Friction Slope Method=2
Unsteady Bridges Friction Slope Method=1
Global Log Level=0
CheckData=False
Run HTab=0
Run UNet=0
Run PostProcess=0
UNET Theta=0
UNET Theta Warmup=0
UNET ZTol=0
UNET ZSATol=0
UNET MxIter=0
UNET MaxInSteps=0
UNET DtIC=0
UNET DtMin=0
UNET MaxCRTS=0
UNET WFStab=0
UNET SFStab=0
UNET WFX=0
UNET SFX=0
UNET DSS MLevel=0
UNET DZMax Abort=0
UNET Convert EG Bridges=0
UNET Use Existing IB Tables=0
UNET Froude Limit=0
UNET Froude Power=0
Write IC File=0
Echo Input=False
Echo Output=False
Write Detailed=0

--- Sims Fork.f01 (steady flow) ---

Flow Title=NFF Regression Equation
Program Version=4.00
Number of Profiles=1
Profile Names=P100yr
River Rch & RM=Sims Fork,Main      ,20073.9
636.7101
River Rch & RM=Sims Fork,Main      ,19263.2
651.1993
River Rch & RM=Sims Fork,Main      ,18376.7
714.9470
River Rch & RM=Sims Fork,Main      ,17784.1
759.6604
River Rch & RM=Sims Fork,Main      ,15698
819.6594
River Rch & RM=Sims Fork,Main      ,15375.8
1046.079
River Rch & RM=Sims Fork,Main      ,13218.3
1140.505
River Rch & RM=Sims Fork,Main      ,10952.6
1221.524
River Rch & RM=Sims Fork,Main      ,10647.6
1458.775
River Rch & RM=Sims Fork,Main      ,6139
1603.897
River Rch & RM=Sims Fork,Main      ,196.7
1779.898
Boundary for River Rch & Prof#=Sims Fork,Main      ,1
Up Type=0
Dn Type=3
Dn Slope=0.022984

--- Sims Fork.g01 (geometry) ---

Geom Title=Geometry
Program Version=4.00

River Reach=Sims Fork       ,Main
Reach XY= 30
     1712520.554       197261.89     1712359.659      197053.839
      1711437.08      196511.443     1710954.995      195292.542
     1710548.963      193511.932     1709782.475      192778.489
     1709168.697      192493.621     1708114.382         192221.
     1707456.428         192314.     1706760.686      192736.081
     1706035.237       192906.54     1705854.661      193086.879
      1705533.01      193022.421     1705195.515      193190.696
      1704772.93      193178.032       1704022.9      192163.845
      1703964.45      191979.835     1704091.515      191434.578
     1703900.927      190900.523     1703314.279      190554.656
      1703291.91      190388.686     1702622.978      190092.826
      1702410.53      189897.193     1702110.635      189098.448
     1701317.901      188413.727     1701056.647      187801.755
     1700623.595      187620.023     1700089.295       187779.56
     1699710.357      187509.704     1699446.505       187701.76

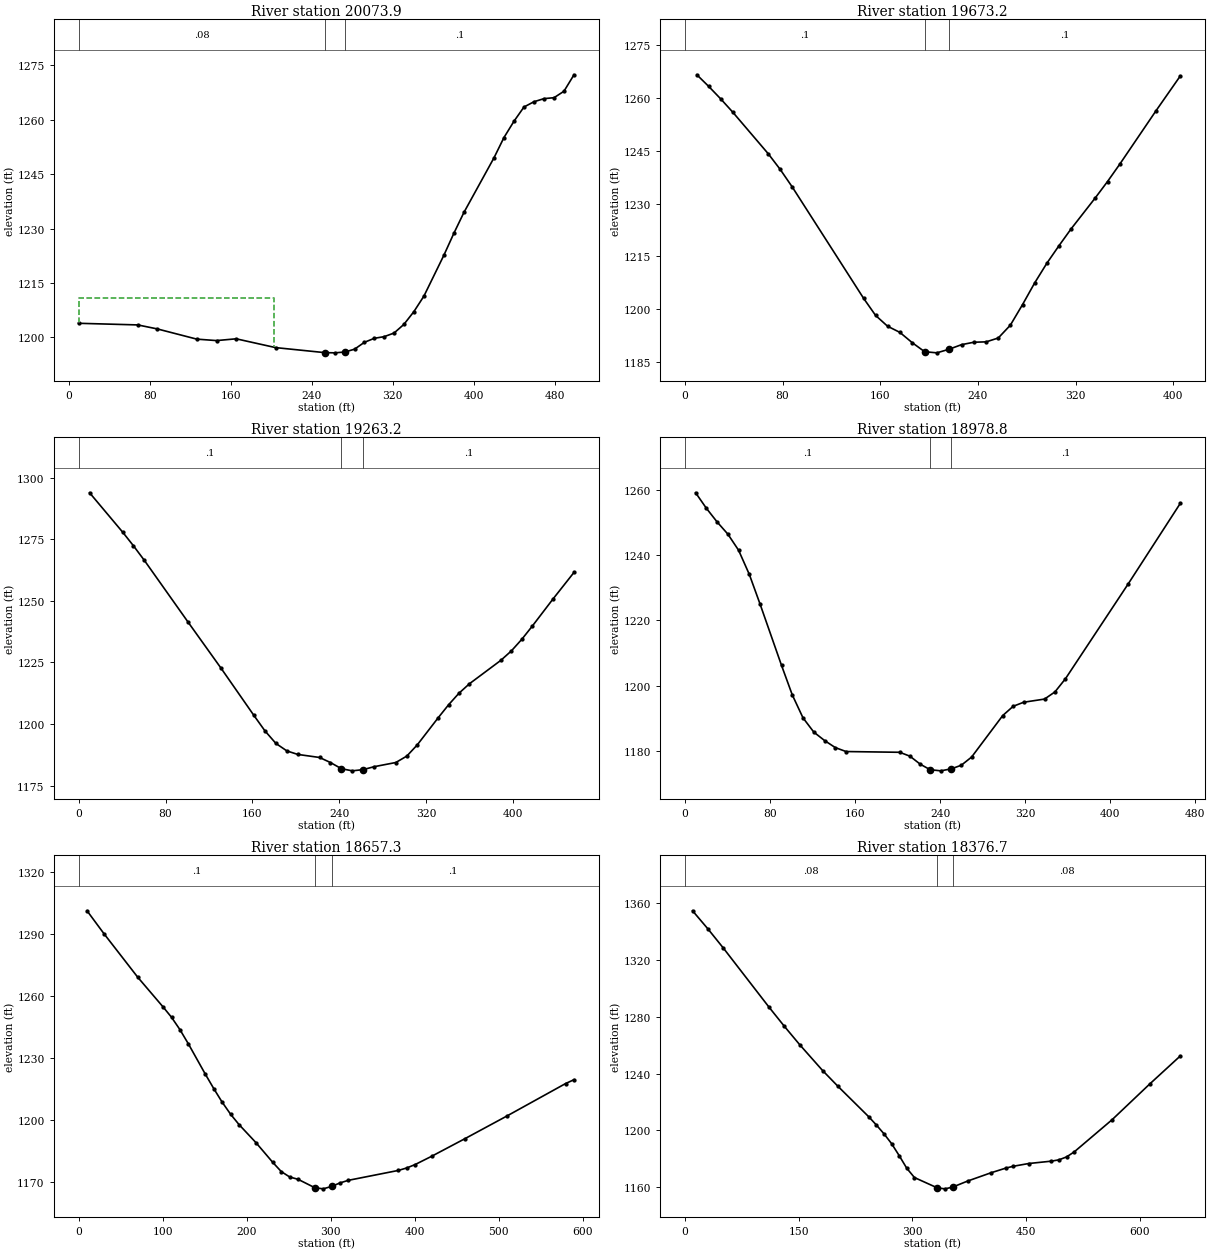
Type RM Length L Ch R = 1 ,20073.9 ,411.3,400.7,390.1
XS GIS Cut Line= 4
     1712764.513      197188.195     1712599.586      197199.976
     1712462.147      197292.256      1712377.72      197437.549
#Sta/Elev= 30
     9.7 1203.89    68.1 1203.44    87.5 1202.33   126.4 1199.52   145.9 1199.12
   165.3 1199.61   204.3 1197.18   252.7  1195.8   262.7 1195.74   272.7 1195.97
   282.2 1196.75   291.9 1198.64   301.7 1199.75   311.4  1200.2   321.2  1201.2
   330.9 1203.58   340.8 1207.11   350.7 1211.39   370.4 1222.65   380.3 1228.73
   390.2 1234.46   419.9 1249.53   429.7  1255.1   439.6  1259.6   449.5 1263.54
   459.4    1265   469.3 1265.85   479.2 1266.11     489 1267.89   498.9 1272.43
#Mann= 3 , 0 , 0
     9.7     .08       0   252.7    .045       0   272.7      .1       0
#XS Ineff= 2 , 0
          203.02    1211
Permanent Ineff=
       F       F
Bank Sta=252.7,272.7
XS Rating Curve= 0 ,0
Exp/Cntr=0.3,0.1

Type RM Length L Ch R = 1 ,19673.2 ,409.5,410,410.6
XS GIS Cut Line= 4
     1712332.561      196795.511     1712255.987      196942.768
     1712220.646      197015.414     1712144.073      197154.817
#Sta/Elev= 30
     9.8 1266.55    19.5 1263.25    29.3 1259.72    39.1 1255.98    68.3 1244.12
    78.1 1239.67    87.9 1234.72   146.4 1203.08   156.2 1198.24     166 1195.17
   176.1 1193.42   186.2  1190.5   196.4 1187.93   206.4 1187.61   216.4 1188.63
   226.6 1189.93   236.7 1190.62   246.8 1190.73   256.7 1191.82   266.6 1195.46
   276.6 1201.31   286.5 1207.44   296.5 1213.04   306.4    1218   316.3 1222.77
   336.2 1231.61   346.2 1236.24   356.1  1241.1   385.9 1256.32   405.8  1266.2
#Mann= 3 , 0 , 0
       0      .1       0   196.4    .045       0   216.4      .1       0
Bank Sta=196.4,216.4
XS Rating Curve= 0 ,0
Exp/Cntr=0.3,0.1

Type RM Length L Ch R = 1 ,19263.2 ,284.5,284.4,284.3
XS GIS Cut Line= 4
     1711986.999      196569.718     1711900.523      196740.809
      1711849.56      196838.706     1711788.694      196980.073
#Sta/Elev= 30
    10.1 1293.82    40.4 1277.93    50.4 1272.36    60.5 1266.41   100.9 1241.27
   131.2  1222.6   161.4 1203.48   171.5 1197.25   181.6 1192.15   191.7 1189.11
   201.7 1187.69   221.8 1186.45   231.8  1184.4   241.9  1181.9   251.9 1181.03
   261.9 1181.52     272 1182.71     292 1184.41   302.1 1187.01   311.7 1191.54
   330.9 1202.51   340.6 1207.85   350.2 1212.55   359.8 1216.37   388.6 1225.83
   398.3 1229.65   407.9 1234.35   417.5 1239.67   436.7 1250.75     456 1261.52
#Mann= 3 , 0 , 0
       0      .1       0   241.9    .045       0   261.9      .1       0
Bank Sta=241.9,261.9
XS Rating Curve= 0 ,0
Exp/Cntr=0.3,0.1

Type RM Length L Ch R = 1 ,18978.8 ,313.6,321.6,329.5
XS GIS Cut Line= 4
     1711747.462       196455.84     1711639.474      196626.657
     1711604.132      196695.377      1711557.01      196876.011
#Sta/Elev= 30
    10.1 1259.23    20.2 1254.47    30.3 1250.27    40.4 1246.53    50.5 1241.58
    60.6 1234.15    70.7 1225.04    90.9 1206.19     101 1197.14   111.1 1190.07
   121.3 1185.68   131.4  1183.1   141.5 1180.93   151.6 1179.72   202.1 1179.49
   211.7 1178.29   221.4 1175.83   230.7 1174.14   240.7 1173.79   250.7 1174.41
     260 1175.51   269.7 1178.02     299 1190.78   308.8 1193.62   318.7 1194.87
   338.3 1195.84   348.1 1198.04     358 1202.09   416.9 1231.17     466 1255.96
#Mann= 3 , 0 , 0
       0      .1       0   230.7    .045       0   250.7      .1       0
Bank Sta=230.7,250.7
XS Rating Curve= 0 ,0
Exp/Cntr=0.3,0.1

Type RM Length L Ch R = 1 ,18657.3 ,274.5,280.5,286.6
XS GIS Cut Line= 4
     1711641.437      196259.498     1711431.351      196414.608
     1711370.485      196465.657     1711176.107      196620.767
#Sta/Elev= 30
      10 1301.12    30.1 1290.05    70.3 1268.95   100.4 1254.58   110.5 1249.55
   120.5 1243.57   130.6 1236.64   150.7 1222.01   160.7 1215.04   170.7 1208.46
   180.8 1202.58   190.8 1197.58   210.9 1188.86     231 1179.25   241.1  1174.8
   251.1 1172.19   261.1 1171.06   280.9 1167.01   290.9 1166.45   300.9 1167.61
   310.8 1169.29   320.7 1170.56   380.4 1175.37   390.3 1176.56   400.3 1178.21
   420.2 1182.27   459.9 1190.82   509.7 1201.77   579.3 1217.44   589.3 1219.31
#Mann= 3 , 0 , 0
       0      .1       0   280.9    .045       0   300.9      .1       0
Bank Sta=280.9,300.9
XS Rating Curve= 0 ,0
Exp/Cntr=0.3,0.1

Type RM Length L Ch R = 1 ,18376.7 ,342.7,345.4,348
XS GIS Cut Line= 4
      1711631.62        196076.9     1711378.339      196145.619
     1711248.753      196200.595     1711007.253      196265.388
#Sta/Elev= 30
    10.1 1354.68    30.3 1341.96    50.5 1328.56     111 1286.76   131.2  1273.3
   151.4 1260.37   181.7 1242.12   201.9 1231.03   242.3  1209.7   252.3 1203.94
   262.4 1197.71   272.5 1190.75   282.5 1182.33   292.6 1173.35   302.7 1166.83
   332.9 1159.55   342.9 1158.88   352.9 1160.08     373  1164.4   403.2 1170.11
   423.2 1173.49   433.2 1174.79   453.2  1176.7   483.2 1178.37   493.2  1179.3
   503.2 1181.35   513.2 1184.82   563.2  1207.5   613.2 1232.84   653.2 1252.44
#Mann= 3 , 0 , 0
       0     .08       0   332.9    .045       0   352.9     .08       0
Bank Sta=332.9,352.9
XS Rating Curve= 0 ,0
Exp/Cntr=0.3,0.1

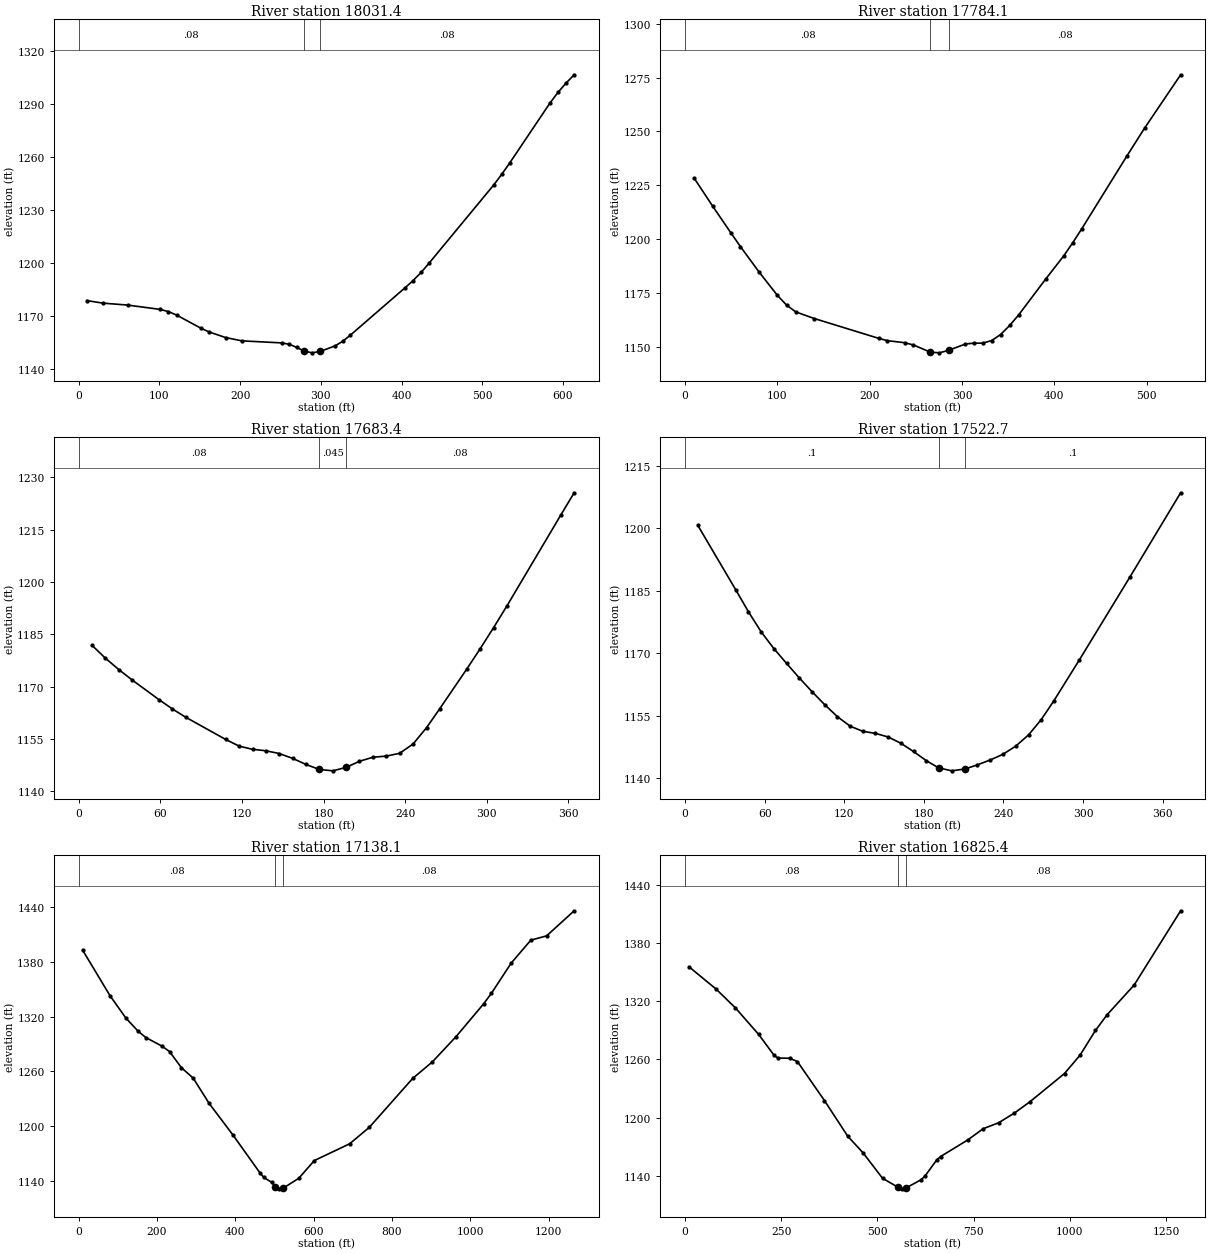
Type RM Length L Ch R = 1 ,18031.4 ,249,247.2,245.5
XS GIS Cut Line= 4
     1711436.172      195729.377     1711232.147      195840.854
      1711095.43      195878.715     1710870.371      195960.745
#Sta/Elev= 30
    10.1 1178.74    30.3 1177.29    60.7 1176.21   101.1 1173.75   111.2 1172.52
   121.3 1170.57   151.6 1163.11   161.7    1161     182 1157.88   202.2 1155.99
   251.4 1154.84   260.9 1154.06   270.3 1152.27   279.2 1150.26   289.2 1149.22
   299.2 1150.02   317.6 1153.11   327.1 1155.73   336.5 1159.15   404.3 1185.95
   414.3 1190.01   424.3 1194.65   434.2 1199.92   514.1 1243.99   524.1 1250.04
   534.1 1256.53     584 1290.41   593.9  1296.4   603.9 1301.66   613.9 1306.32
#Mann= 3 , 0 , 0
       0     .08       0   279.2    .045       0   299.2     .08       0
Bank Sta=279.2,299.2
XS Rating Curve= 0 ,0
Exp/Cntr=0.3,0.1

Type RM Length L Ch R = 1 ,17784.1 ,101.2,100.7,100.2
XS GIS Cut Line= 4
     1711335.211      195506.422     1711150.117      195605.279
     1711044.949      195645.243     1710853.544      195741.997
#Sta/Elev= 30
      10  1228.2      30 1215.24      50 1202.67      60 1196.51    79.9 1184.87
    99.9 1173.94   109.9 1169.38   119.9 1166.21   139.9 1163.14   209.8 1153.92
   219.2 1152.85     238  1151.9   247.3 1150.86   265.5 1147.55   275.5  1147.2
   285.5 1148.38   303.6 1151.29     313 1151.71   322.3 1151.69   332.1  1152.9
   341.8 1155.71   351.6 1159.91   361.3  1164.8   390.6 1181.46   410.1  1192.2
   419.8 1198.27   429.6 1204.75   478.3 1238.43   497.8  1251.6   536.8 1276.34
#Mann= 3 , 0 , 0
       0     .08       0   265.5    .045       0   285.5     .08       0
Bank Sta=265.5,285.5
XS Rating Curve= 0 ,0
Exp/Cntr=0.3,0.1

Type RM Length L Ch R = 1 ,17683.4 ,160.3,160.7,161.1
XS GIS Cut Line= 3
     1711227.941      195464.355     1711009.192      195552.695
     1710882.991      195575.832
#Sta/Elev= 30
     9.8 1181.84    19.7 1178.11    29.5 1174.87    39.3 1171.89      59 1166.25
    68.8  1163.6    78.6 1161.21   108.1 1154.81     118 1152.89   127.8 1151.99
   137.6 1151.57   147.4 1150.78   157.3 1149.38   167.1 1147.64   176.8 1146.22
   186.8 1145.81   196.8 1146.82   206.4 1148.56   216.3 1149.71   226.1 1150.04
   235.9 1150.83   245.8 1153.51   255.7 1158.19   265.5 1163.68   285.3 1175.03
   295.1 1180.83     305 1186.91   314.9  1193.2   354.3 1219.15   364.2 1225.58
#Mann= 3 , 0 , 0
       0     .08       0   176.8    .045       0   196.8     .08       0
Bank Sta=176.8,196.8
XS Rating Curve= 0 ,0
Exp/Cntr=0.3,0.1

Type RM Length L Ch R = 1 ,17522.7 ,379.5,384.6,389.8
XS GIS Cut Line= 4
     1711192.184      195357.084     1711030.226      195371.807
     1710931.368      195409.668     1710832.511      195445.425
#Sta/Elev= 30
     9.6 1200.69    38.3 1185.19    47.8 1179.95    57.4 1175.13      67 1171.12
    76.5 1167.59    86.1 1164.11    95.7 1160.81   105.2 1157.71   114.8 1154.82
   124.4 1152.54   133.9 1151.31   143.5  1150.8   153.1 1149.94   162.6 1148.45
   172.2 1146.46   181.9 1144.25   191.1 1142.54   201.1 1141.82   211.1 1142.27
   220.4 1143.26     230 1144.42   239.6 1145.78   249.2 1147.73   258.9 1150.43
   268.5 1154.11     278 1158.61   297.2 1168.41   335.4 1188.33   373.6 1208.52
#Mann= 3 , 0 , 0
       0      .1       0   191.1    .045       0   211.1      .1       0
Bank Sta=191.1,211.1
XS Rating Curve= 0 ,0
Exp/Cntr=0.3,0.1

Type RM Length L Ch R = 1 ,17138.1 ,315,312.7,310.3
XS GIS Cut Line= 4
     1711404.282      194898.305     1711044.717      194999.159
     1710807.931      195025.468     1710158.959      195104.397
#Sta/Elev= 30
    10.1 1392.79    80.7 1342.48   121.1 1318.16   151.4  1304.2   171.6 1297.06
     212 1287.88   232.1 1281.74   262.4 1264.13   292.7 1252.56   333.1 1225.09
   393.3 1190.86   462.8  1149.1   472.7    1144   492.6 1138.71   502.4 1134.05
   512.4 1131.49   522.4 1132.29   562.1    1143   601.8 1162.42   692.1 1180.79
   742.4 1198.85   853.1 1252.35   903.4 1270.46   963.7 1298.04  1034.1 1333.91
  1054.2 1345.54  1104.5  1378.5  1154.8 1403.67    1195 1408.33  1265.4 1435.79
#Mann= 3 , 0 , 0
       0     .08       0   502.4    .045       0   522.4     .08       0
Bank Sta=502.4,522.4
XS Rating Curve= 0 ,0
Exp/Cntr=0.3,0.1

Type RM Length L Ch R = 1 ,16825.4 ,431.4,430.3,429.1
XS GIS Cut Line= 3
     1711404.282      194600.129     1710978.943      194679.058
     1710145.804      194871.995
#Sta/Elev= 30
    10.1  1355.5    80.5 1332.53   130.8 1313.12   191.1 1285.82   231.4 1264.19
   241.5 1261.41   271.6 1261.23   291.8 1257.87   362.2  1217.6   422.5 1180.96
   462.8 1163.61   513.1 1137.52   553.4 1128.26   563.4 1126.63   573.4  1127.4
   613.7 1136.08   623.8 1140.01   653.9 1156.41     664 1159.93   734.4 1176.98
   774.7 1188.61   814.9 1194.75   855.2 1204.57   895.4 1216.13     986  1245.5
  1026.2 1264.29  1066.4 1289.86  1096.6 1306.02  1167.1 1336.74  1287.8 1413.22
#Mann= 3 , 0 , 0
       0     .08       0   553.4    .045       0   573.4     .08       0
Bank Sta=553.4,573.4
XS Rating Curve= 0 ,0
Exp/Cntr=0.3,0.1

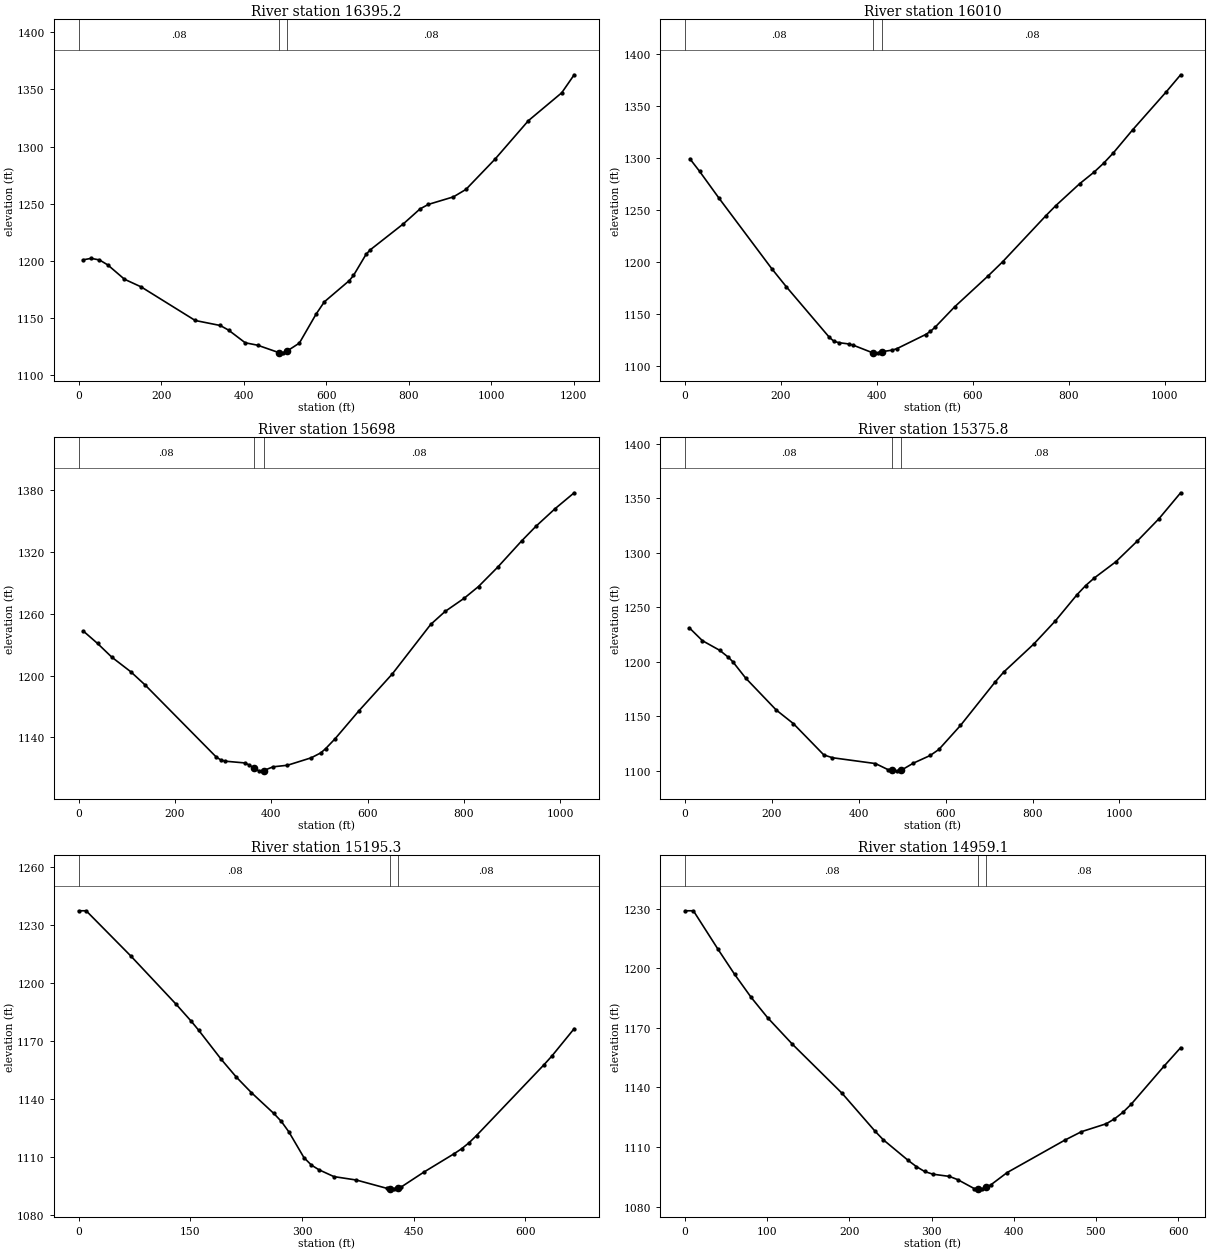
Type RM Length L Ch R = 1 ,16395.2 ,385.9,385.1,384.4
XS GIS Cut Line= 2
     1711246.425       194148.48     1710093.185      194486.121
#Sta/Elev= 30
    10.1 1200.66    30.3 1201.99    50.5 1200.61    70.7 1196.24   111.1 1183.71
   151.5 1177.01   282.7 1147.55   343.3 1143.17   363.5 1139.13   403.9 1128.03
   434.2 1125.87   484.8 1119.48   494.8  1119.2   504.8 1120.62   535.2 1127.72
   575.6 1153.03   595.8  1163.9   656.4 1182.54   666.5 1187.01   696.8 1205.42
   706.9 1209.41   787.6 1232.29     828 1245.37   848.2  1249.3   908.8 1255.89
   939.1  1262.4  1009.8 1288.99  1090.6 1322.67  1171.4 1347.09  1201.6 1362.88
#Mann= 3 , 0 , 0
       0     .08       0   484.8    .045       0   504.8     .08       0
Bank Sta=484.8,504.8
XS Rating Curve= 0 ,0
Exp/Cntr=0.3,0.1

Type RM Length L Ch R = 1 ,16010   ,312.1,312,312
XS GIS Cut Line= 2
     1711049.102        193793.3      1710071.26      194126.555
#Sta/Elev= 30
      10 1299.23    30.1 1287.27    70.2 1261.72   180.5 1193.84   210.6 1176.62
   300.9 1127.72   310.9 1123.85     321 1122.69     341 1121.47     351 1120.19
   391.2 1112.94   401.2 1112.93   411.2 1114.12   431.3 1115.47   441.3 1116.89
   501.5 1130.52   511.5 1133.57   521.6 1137.72   561.7    1157   631.9 1186.86
     662 1200.34   752.2 1244.61   772.3 1254.04   822.4 1275.24   852.5 1286.39
   872.6    1295   892.7 1304.84   932.8 1326.91    1003 1363.47  1033.1  1379.9
#Mann= 3 , 0 , 0
       0     .08       0   391.2    .045       0   411.2     .08       0
Bank Sta=391.2,411.2
XS Rating Curve= 0 ,0
Exp/Cntr=0.3,0.1

Type RM Length L Ch R = 1 ,15698   ,330.5,322.2,313.8
XS GIS Cut Line= 4
     1710961.403      193582.823     1710676.382      193591.593
     1710395.746      193688.061     1710066.875      193990.622
#Sta/Elev= 30
     9.8 1243.08    39.3 1231.09    68.8 1217.82   108.2 1203.66   137.7 1190.97
   285.2 1121.15     295 1118.08   304.9 1116.85   344.5  1115.2   354.4 1113.19
   364.2 1109.95   374.2 1107.51   384.2  1107.8   403.9 1111.43   433.5 1112.92
     483 1120.18   502.8 1124.95   512.7 1128.99   532.5 1138.67   581.9 1165.76
   651.4 1201.62   730.9 1249.54   760.7  1262.1   800.4 1274.93   830.2 1286.34
   869.9 1305.04   919.6 1330.51   949.3 1344.73   989.1 1361.81  1028.8 1377.28
#Mann= 3 , 0 , 0
       0     .08       0   364.2    .045       0   384.2     .08       0
Bank Sta=364.2,384.2
XS Rating Curve= 0 ,0
Exp/Cntr=0.3,0.1

Type RM Length L Ch R = 1 ,15375.8 ,184,180.6,177.1
XS GIS Cut Line= 4
     1710790.391      193004.011       1710496.6      193289.032
     1710382.591       193394.27     1710018.641      193841.534
#Sta/Elev= 30
      10 1230.89    39.9  1219.2    79.9 1210.33    99.8 1203.94   109.8 1199.93
   139.8 1184.76   209.7 1155.69   249.6 1143.07   319.5 1114.42   339.4 1111.87
   438.4 1106.52   467.5 1100.92   476.9 1100.19   486.9 1099.85   496.9 1100.22
   525.7 1106.91   564.5 1113.96   584.4 1119.46   634.1 1141.45   713.6 1181.16
   733.5 1190.35   803.1 1216.21   852.8 1237.43   902.5 1261.39   922.4 1269.76
   942.3 1276.71     992  1291.6  1041.7 1310.74  1091.4 1331.15  1141.1 1354.84
#Mann= 3 , 0 , 0
       0     .08       0   476.9    .045       0   496.9     .08       0
Bank Sta=476.9,496.9
XS Rating Curve= 0 ,0
Exp/Cntr=0.3,0.1

Type RM Length L Ch R = 1 ,15195.3 ,236.9,236.2,235.4
XS GIS Cut Line= 2
     1710555.174      192895.938     1710149.888      193423.673
#Sta/Elev= 30
       0 1237.15    10.1 1237.15    70.6 1213.57   131.1 1188.75   151.2 1180.06
   161.3 1175.35   191.6  1160.3   211.7  1151.2   231.9 1143.18   262.1 1132.38
   272.2 1128.27   282.3 1122.86   302.5 1109.59   312.5 1105.71   322.6  1103.3
   342.8 1099.74     373 1097.97   413.4 1093.73   418.4 1093.58   423.4 1093.42
   428.4 1093.94   433.5 1094.47   463.8 1102.12   504.1 1111.55   514.2 1114.12
   524.3 1117.25   534.3 1120.99   625.1 1157.66   635.2 1161.95   665.4 1176.21
#Mann= 3 , 0 , 0
       0     .08       0   418.4    .045       0   428.4     .08       0
Bank Sta=418.4,428.4
XS Rating Curve= 0 ,0
Exp/Cntr=0.3,0.1

Type RM Length L Ch R = 1 ,14959.1 ,114.3,116.3,118.3
XS GIS Cut Line= 2
     1710305.104      192820.055      1709953.28      193309.848
#Sta/Elev= 30
       0  1228.9    10.1  1228.9    40.2 1209.44    60.3 1196.89    80.4 1185.31
   100.5 1175.05   130.7 1161.69     191 1137.06   231.2 1117.95   241.2 1113.64
   271.4 1103.29   281.4 1100.16   291.5 1097.67   301.5 1096.32   321.6  1095.2
   331.7 1093.59   351.8 1089.09   356.8 1089.02   361.8 1088.94   366.8 1089.91
   371.9 1090.89     392 1097.15   462.3 1113.49   482.4 1117.71   512.6  1121.7
   522.6 1124.16   532.7 1127.39   542.8 1131.47     583 1150.74   603.1 1159.99
#Mann= 3 , 0 , 0
       0     .08       0   356.8    .045       0   366.8     .08       0
Bank Sta=356.8,366.8
XS Rating Curve= 0 ,0
Exp/Cntr=0.3,0.1

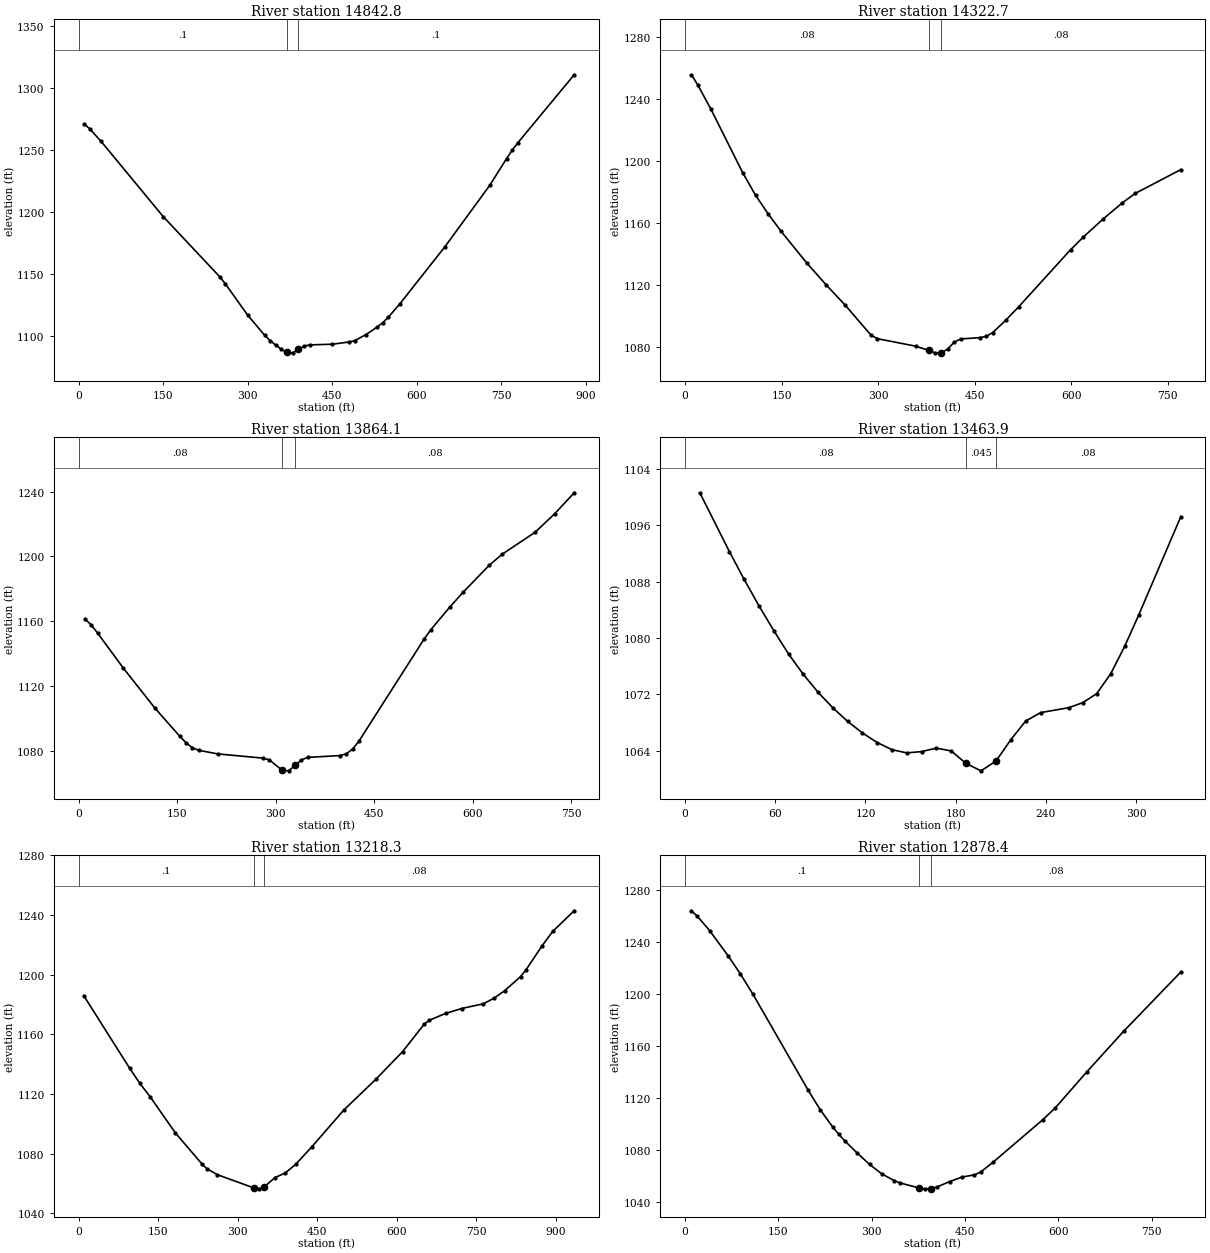
Type RM Length L Ch R = 1 ,14842.8 ,522.7,520.1,517.4
XS GIS Cut Line= 4
     1710281.738      192754.069     1710062.491      192973.316
     1709970.407      193078.555     1709694.155      193407.425
#Sta/Elev= 30
      10 1271.16      20 1267.19      40 1257.14     150 1196.64   250.1 1148.23
   260.1 1142.58   300.1 1117.09     330    1101     340 1096.51     350 1092.93
     360 1089.53     370 1087.11     380 1086.78     390 1089.55     400 1092.17
   409.9 1093.18   449.9 1093.74   479.9  1095.5   489.9 1096.63   509.8 1101.42
   529.8 1107.59   539.8 1111.11   549.8 1115.61   569.8 1126.14   649.7  1172.1
   729.6  1221.8   759.5  1243.4   769.5 1250.15   779.5 1256.13   879.4  1310.9
#Mann= 3 , 0 , 0
       0      .1       0     370    .045       0     390      .1       0
Bank Sta=370,390
XS Rating Curve= 0 ,0
Exp/Cntr=0.3,0.1

Type RM Length L Ch R = 1 ,14322.7 ,462.7,458.6,454.5
XS GIS Cut Line= 4
     1709834.474      192420.813     1709681.001      192653.215
     1709571.377      192819.843     1709413.519        193065.4
#Sta/Elev= 30
     9.9 1255.35    19.9 1248.64    39.8 1233.44    89.5 1192.18   109.4 1177.69
   129.3 1165.45   149.2 1154.36     189 1133.97   218.8 1120.02   248.7 1106.79
   288.5 1087.57   298.4 1085.17   358.3 1080.31   378.2 1077.63   388.2 1076.01
   398.2 1076.06   408.1 1078.44   418.1 1082.92   428.1 1084.96     458 1085.82
     468 1086.71     478  1089.1   498.1    1097   518.2 1105.66   598.8 1142.48
   618.9 1150.78   649.1 1162.19   679.3 1172.76   699.4 1178.83   769.9 1194.14
#Mann= 3 , 0 , 0
       0     .08       0   378.2    .045       0   398.2     .08       0
Bank Sta=378.2,398.2
XS Rating Curve= 0 ,0
Exp/Cntr=0.3,0.1

Type RM Length L Ch R = 1 ,13864.1 ,404.2,400.2,396.2
XS GIS Cut Line= 4
     1709365.285      192241.031     1709268.816      192407.659
     1709172.347      192653.215     1709010.105      192903.157
#Sta/Elev= 30
     9.6 1161.34    19.3 1157.53    28.9 1152.61    67.4 1131.29   115.5 1106.55
     154 1088.81   163.7 1084.75   173.3  1081.7   182.9 1080.17   212.1 1077.94
   280.5 1075.36   290.3 1074.29   309.6  1067.9   319.6  1067.5   329.6  1070.8
   339.1 1074.22   348.9 1075.82   397.7 1076.92   407.5 1077.97   417.3 1081.04
   427.1 1086.12   525.9  1148.9   535.8 1154.52   565.6 1168.94   585.5 1177.92
   625.2 1194.56   645.1 1201.39   694.8 1214.84   724.5 1226.23   754.3 1239.24
#Mann= 3 , 0 , 0
       0     .08       0   309.6    .045       0   329.6     .08       0
Bank Sta=309.6,329.6
XS Rating Curve= 0 ,0
Exp/Cntr=0.3,0.1

Type RM Length L Ch R = 1 ,13463.9 ,247,245.6,244.2
XS GIS Cut Line= 3
     1708883.358      192227.688       1708849.1      192381.163
     1708835.397       192459.27
#Sta/Elev= 30
     9.8 1100.61    29.5 1092.25    39.3 1088.31    49.1 1084.58      59 1081.05
    68.8 1077.74    78.6 1074.85    88.5 1072.29    98.3 1070.08   108.1 1068.17
   117.9 1066.53   127.8 1065.16   137.6 1064.15   147.4 1063.69   157.3 1063.87
   167.2 1064.37   177.1 1063.96   186.9 1062.19   196.9 1061.14   206.9 1062.54
   216.7 1065.56   226.6 1068.21   236.6 1069.41   255.2  1070.1   264.5 1070.81
   273.8 1072.09   283.1 1074.89   292.5 1078.82   301.8 1083.26   329.7 1097.17
#Mann= 3 , 0 , 0
       0     .08       0   186.9    .045       0   206.9     .08       0
Bank Sta=186.9,206.9
XS Rating Curve= 0 ,0
Exp/Cntr=0.3,0.1

Type RM Length L Ch R = 1 ,13218.3 ,339.6,339.9,340.3
XS GIS Cut Line= 4
     1708697.403      192050.286     1708618.474      192225.683
     1708592.164       192471.24     1708587.779      192966.738
#Sta/Elev= 30
     9.6 1185.94    96.2 1137.27   115.4 1127.16   134.6  1118.3   182.7 1093.83
   231.9  1073.4   241.7 1069.99   261.5 1065.94   330.5 1057.05   340.5 1056.43
   350.5 1057.79   370.2 1063.97   389.9 1067.06   409.7 1072.93   439.3 1084.36
     500 1109.16   560.7 1129.87   611.2 1148.42   651.7 1166.71   661.8 1169.48
   692.1 1173.96   722.5  1177.3   762.9  1180.4   783.1 1184.06   803.4 1189.16
   833.7  1198.7   843.8 1203.15   874.1 1219.26   894.4 1228.99   934.8  1242.8
#Mann= 3 , 0 , 0
       0      .1       0   330.5    .045       0   350.5     .08       0
Bank Sta=330.5,350.5
XS Rating Curve= 0 ,0
Exp/Cntr=0.3,0.1

Type RM Length L Ch R = 1 ,12878.4 ,594.1,587.1,580
XS GIS Cut Line= 4
     1708418.138       191920.93     1708295.359      192157.717
      1708260.28      192403.274      1708233.97       192683.91
#Sta/Elev= 30
     9.9  1264.3    19.8 1260.06    39.5    1249    69.2 1229.68    88.9  1215.7
   108.7 1200.43   197.6 1126.48   217.3 1111.23   237.1  1098.1     247 1092.38
   256.8 1087.27   276.6 1077.99   296.5 1069.21   316.3 1061.92   336.2 1056.71
   346.1 1054.89   375.8 1051.13   385.8 1050.42   395.8 1050.64   405.6 1051.99
   425.5 1056.06   445.3 1059.53   465.2 1061.16   475.1 1063.35   494.9 1070.82
   575.2 1103.67   595.3 1112.82   645.6 1140.31     706 1172.13   796.6 1217.05
#Mann= 3 , 0 , 0
       0      .1       0   375.8    .045       0   395.8     .08       0
Bank Sta=375.8,395.8
XS Rating Curve= 0 ,0
Exp/Cntr=0.3,0.1

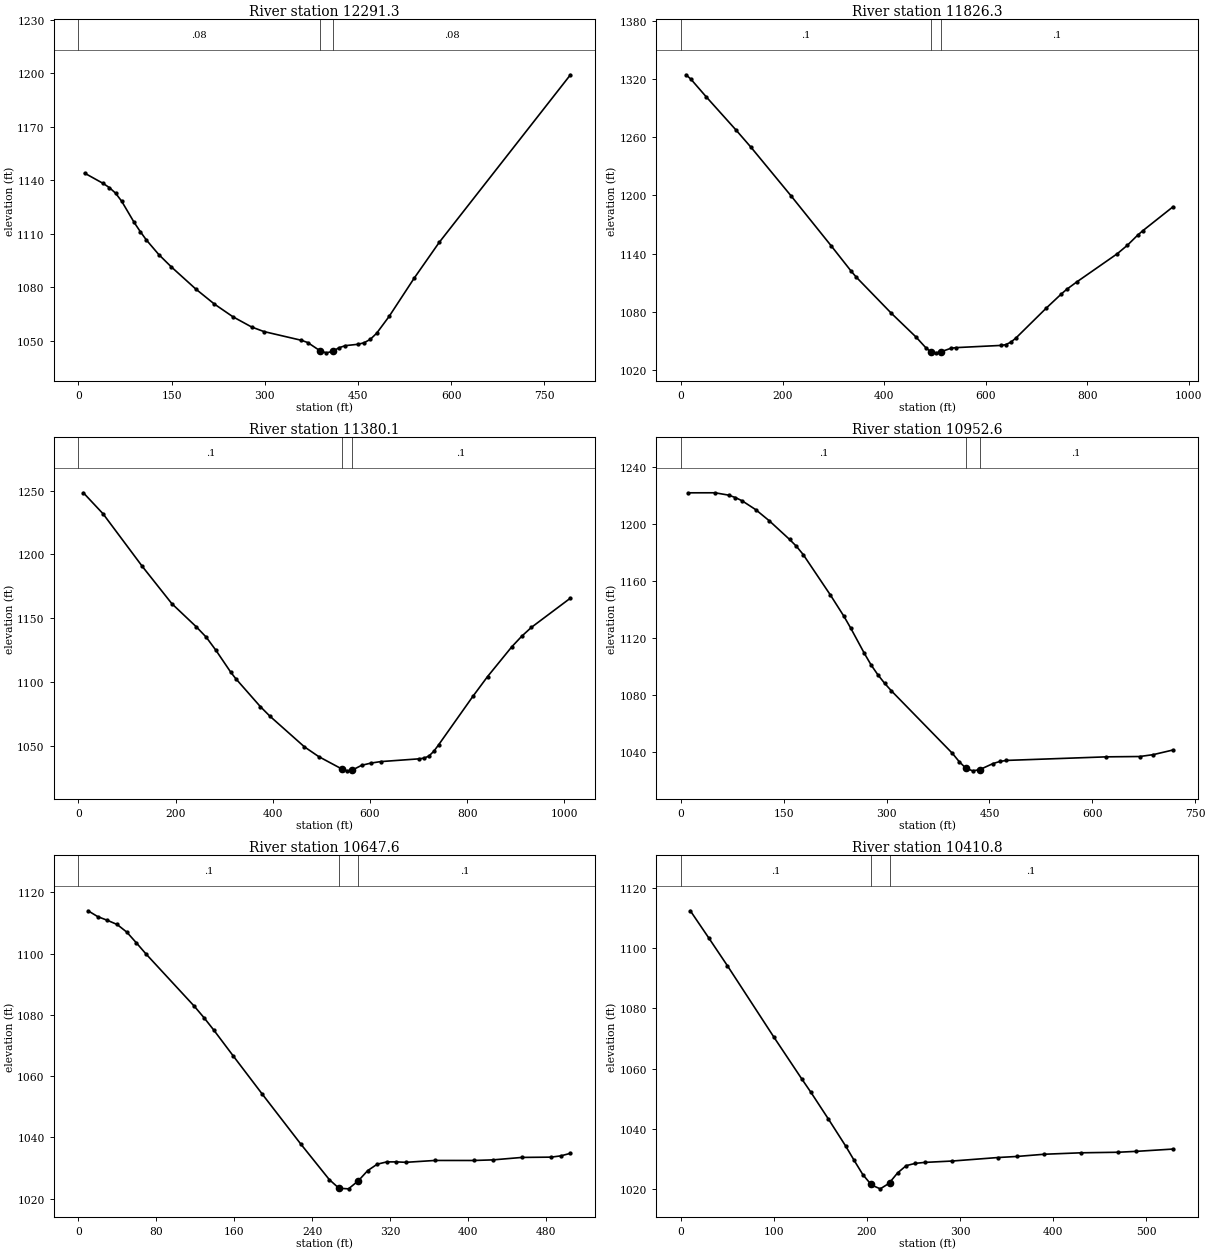
Type RM Length L Ch R = 1 ,12291.3 ,469.8,465,460.1
XS GIS Cut Line= 4
     1707633.233      191881.466     1707685.853      192175.257
     1707742.857      192420.813     1707808.631      192653.215
#Sta/Elev= 30
     9.9 1143.94    39.8 1138.17    49.7 1135.85    59.7 1132.75    69.6 1128.19
    89.5 1116.42    99.5  1111.2   109.4 1106.46   129.3 1098.33   149.2  1091.5
     189 1078.97   218.9 1070.56   248.7 1063.45   278.6 1057.76   298.5 1055.17
     359 1050.26   369.1 1049.01   389.3 1044.31   399.3 1043.24   409.3 1044.11
   419.5 1046.09   429.6 1047.27   449.7 1048.02   459.8 1048.87   469.9 1050.82
     480 1054.19   500.1 1063.62   540.5 1085.09   580.7 1105.09   792.1 1199.06
#Mann= 3 , 0 , 0
       0     .08       0   389.3    .045       0   409.3     .08       0
Bank Sta=389.3,409.3
XS Rating Curve= 0 ,0
Exp/Cntr=0.3,0.1

Type RM Length L Ch R = 1 ,11826.3 ,448.8,446.2,443.6
XS GIS Cut Line= 4
     1707054.421      191977.934     1707212.279       192284.88
     1707343.827      192547.977     1707620.078      192727.759
#Sta/Elev= 30
     9.9 1324.35    19.7 1319.67    49.3 1301.81   108.5 1267.27   138.1 1249.43
     217 1199.33   295.9  1147.9   335.3 1121.74   345.2 1115.69   413.8 1078.69
   462.8 1053.99   482.4 1042.77     492 1038.81     502  1037.7     512 1038.83
   531.5  1042.4   541.3 1043.07   629.5 1045.34   639.3 1046.08   649.3 1048.66
   659.3 1052.86   719.2 1083.78   749.2 1098.52   759.2 1103.03   779.1 1110.71
     859 1139.83     879  1148.6     899 1158.89     909 1163.43   968.9 1188.28
#Mann= 3 , 0 , 0
       0      .1       0     492    .045       0     512      .1       0
Bank Sta=492,512
XS Rating Curve= 0 ,0
Exp/Cntr=0.3,0.1

Type RM Length L Ch R = 1 ,11380.1 ,423.5,427.5,431.6
XS GIS Cut Line= 4
     1706620.312      192157.717     1706843.944      192565.516
     1706953.567      192727.759     1707181.584      192995.241
#Sta/Elev= 30
    10.1 1248.23    50.6 1231.82   131.4 1190.69   192.1 1161.61   242.7 1143.41
   262.9 1135.41   283.1 1125.02   313.4 1108.01   323.5 1103.07   374.1 1081.21
   394.3 1073.54   465.1 1049.65   494.5 1042.04   543.2 1032.14   553.2 1030.94
   563.2 1031.48   582.6 1035.25   602.2 1037.02   621.7 1038.15   701.1 1040.33
   711.1 1040.87   721.2 1042.51   731.2 1046.22   741.2 1051.32   811.5 1089.08
   841.7 1104.55   891.9 1127.97     912 1136.08     932 1143.04  1012.4 1165.92
#Mann= 3 , 0 , 0
       0      .1       0   543.2    .045       0   563.2      .1       0
Bank Sta=543.2,563.2
XS Rating Curve= 0 ,0
Exp/Cntr=0.3,0.1

Type RM Length L Ch R = 1 ,10952.6 ,294.5,304.9,315.4
XS GIS Cut Line= 4
      1706406.58      192408.117     1706482.595      192746.253
     1706540.262      192882.556     1706726.368      193005.753
#Sta/Elev= 30
     9.9 1221.87    49.5  1221.9    69.3 1220.26    79.2 1218.57    89.1 1216.27
   108.9 1210.07   128.7 1202.25   158.4 1189.12   168.3 1184.34   178.2 1178.55
   217.8 1150.19   237.7 1135.13   247.6 1126.82   267.4 1109.17   277.3 1100.98
   287.2 1094.06   297.1 1088.07     307 1082.75   395.9  1038.9   405.8 1033.09
   415.5 1028.49   425.5 1026.61   435.5  1027.4   455.1 1031.71     465 1033.17
   474.8 1033.93   620.7 1036.44   669.2 1036.67   688.7 1037.96   717.8 1041.26
#Mann= 3 , 0 , 0
       0      .1       0   415.5    .045       0   435.5      .1       0
Bank Sta=415.5,435.5
XS Rating Curve= 0 ,0
Exp/Cntr=0.3,0.1

Type RM Length L Ch R = 1 ,10647.6 ,250.7,236.8,223
XS GIS Cut Line= 4
     1706241.444       192609.95      1706233.58      192837.996
     1706220.474      192945.465     1706333.186      193071.283
#Sta/Elev= 30
     9.9 1113.99    19.8 1112.08    29.8 1110.86    39.7 1109.52    49.6 1107.04
    59.5 1103.52    69.4 1099.89   119.1 1082.79     129 1079.07   138.9 1075.09
   158.7 1066.72   188.5 1054.26   228.2  1037.9   257.7 1026.21   267.4 1023.45
   267.6 1023.39   277.4  1023.2   287.4  1025.8   297.1 1029.15   306.9 1031.25
   316.8    1032   326.6    1032   336.4 1031.86   366.3 1032.47     406 1032.46
   425.9 1032.66   455.7 1033.46   485.5 1033.55   495.4 1033.96   505.4  1034.8
#Mann= 3 , 0 , 0
       0      .1       0   267.4    .045       0   287.4      .1       0
Bank Sta=267.4,287.4
XS Rating Curve= 0 ,0
Exp/Cntr=0.3,0.1

Type RM Length L Ch R = 1 ,10410.8 ,129.3,116.9,104.6
XS GIS Cut Line= 4
     1705871.853      192754.117     1705960.974      192861.586
      1706016.02      192948.086     1706286.004      193045.071
#Sta/Elev= 27
      10  1112.4    29.9 1103.35    49.9 1094.15    99.7 1070.54   129.6  1056.7
   139.6 1052.18   158.3 1043.36   176.9 1034.38   186.2 1029.54   195.5 1024.83
   204.2 1021.63   204.9 1021.37   214.2 1020.12   223.5 1021.91   224.2 1022.17
   232.8 1025.39   242.1 1027.82     252 1028.58   261.9 1028.89   291.6 1029.35
   341.1 1030.52   360.9 1030.86   390.5  1031.6   430.1 1032.08   469.7 1032.26
   489.5 1032.56     529 1033.32
#Mann= 3 , 0 , 0
       0      .1       0   204.2    .045       0   224.2      .1       0
Bank Sta=204.2,224.2
XS Rating Curve= 0 ,0
Exp/Cntr=0.3,0.1