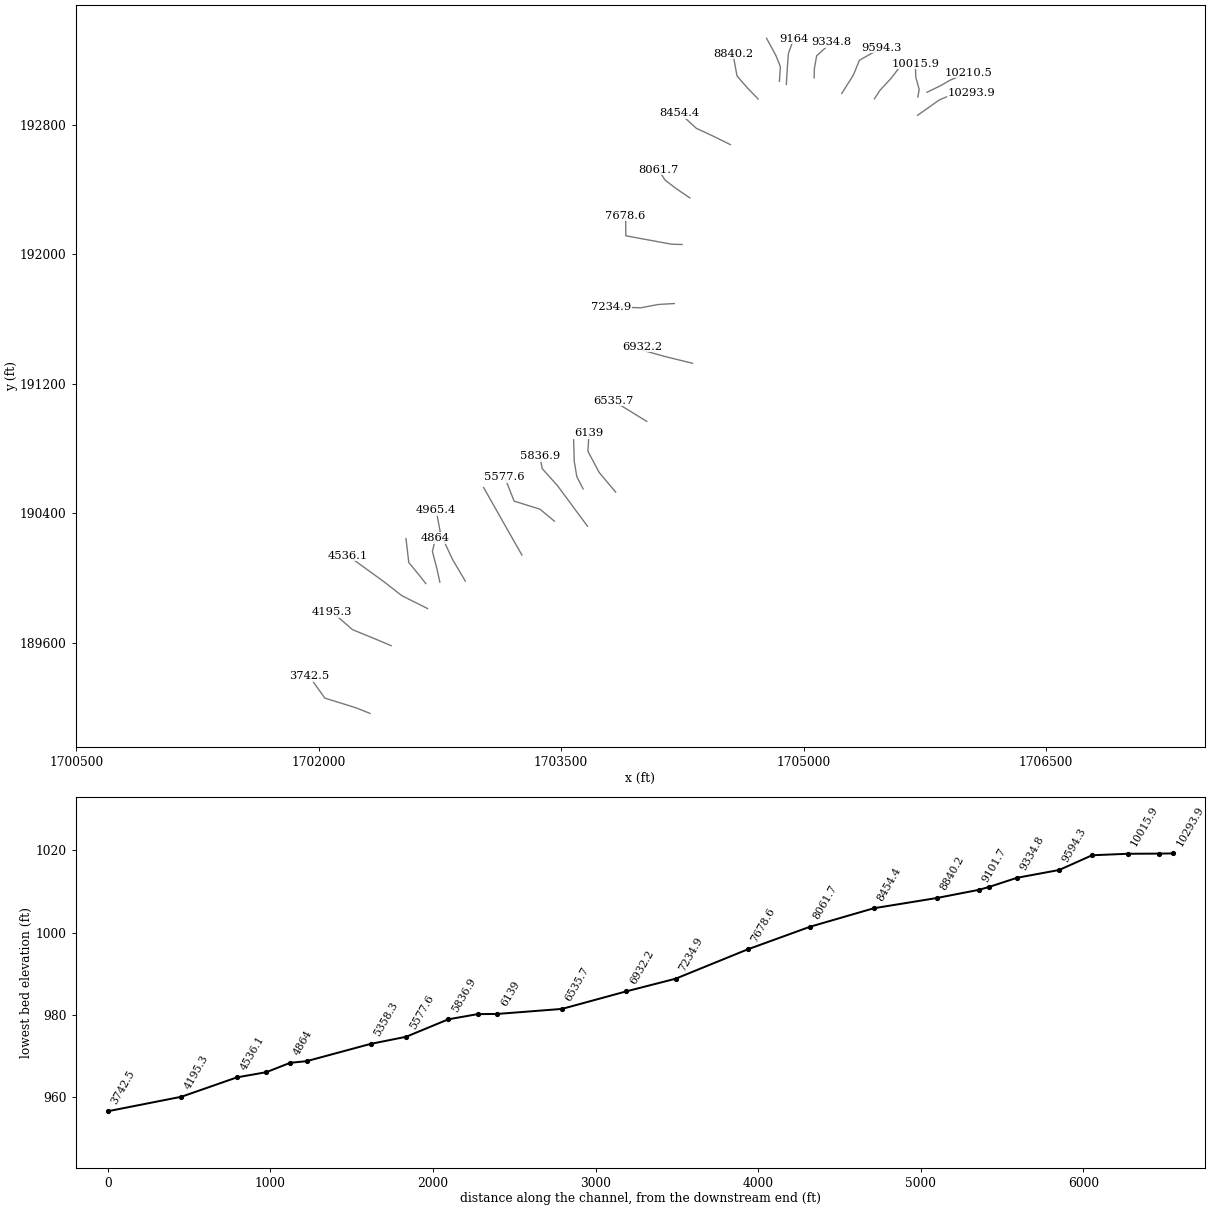
HEC-RAS study Sims Fork.prj: Sims Fork

--- Sims Fork.g01 (geometry) --- (continued)

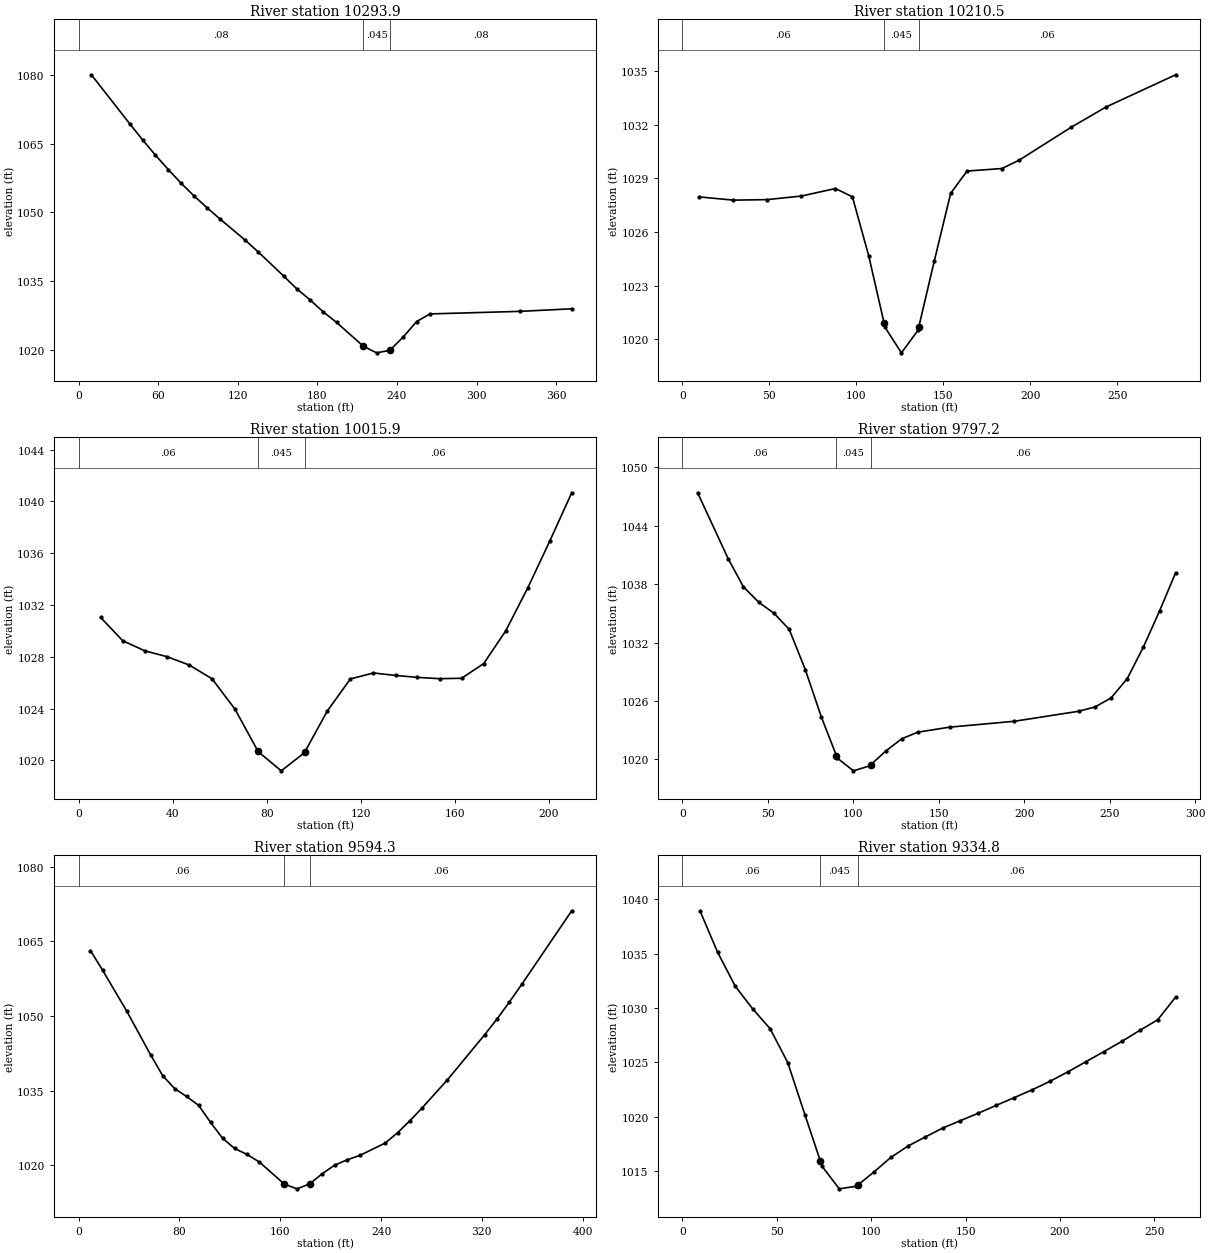
Type RM Length L Ch R = 1 ,10293.9 ,80.8,83.4,86.1
XS GIS Cut Line= 4
     1705705.111       192860.18     1705839.231      192955.133
     1705931.809        192994.3     1706038.631      192995.487
#Sta/Elev= 24
     9.7 1080.08    38.7 1069.33    48.3 1065.85      58  1062.5    67.7 1059.36
    77.3 1056.37      87 1053.61    96.7 1051.05   106.3 1048.63   125.7  1043.9
   135.3 1041.38   154.7 1036.05   164.3 1033.33   174.4 1030.88   184.4 1028.25
   194.5 1025.93   214.6 1020.74   224.6 1019.28   234.6 1019.83   244.7 1022.74
   254.8 1026.12   264.9 1027.79   332.8 1028.35   371.7 1028.91
#Mann= 3 , 0 , 0
       0     .08       0   214.6    .045       0   234.6     .08       0
Bank Sta=214.6,234.6
XS Rating Curve= 0 ,0
Exp/Cntr=0.3,0.1

Type RM Length L Ch R = 1 ,10210.5 ,167.2,194.6,222
XS GIS Cut Line= 4
     1705763.269      193002.609       1705851.1      193045.337
     1705908.071      193078.571      1706019.64      193122.486
#Sta/Elev= 20
     9.8 1027.96    29.3 1027.78    48.8 1027.81    68.4 1028.01    87.9 1028.43
    97.7 1027.97   107.1 1024.66   115.9 1020.91   116.5 1020.65   125.9 1019.23
   135.4 1020.49   135.9 1020.69   144.8 1024.38   154.2 1028.16   163.6 1029.41
   183.6 1029.55   193.6 1030.02   223.6 1031.87   243.6    1033   283.5  1034.8
#Mann= 3 , 0 , 0
       0     .06       0   115.9    .045       0   135.9     .06       0
Bank Sta=115.9,135.9
XS Rating Curve= 0 ,0
Exp/Cntr=0.3,0.1

Type RM Length L Ch R = 1 ,10015.9 ,239.1,218.6,198.2
XS GIS Cut Line= 4
     1705706.464      192973.406       1705715.2      193019.583
     1705694.429      193095.187     1705690.868      193179.457
#Sta/Elev= 24
     9.4 1031.04    18.8 1029.24    28.2 1028.46    37.6 1028.01      47 1027.37
    56.8  1026.3    66.6 1023.93    76.2 1020.74    76.4 1020.67    86.2 1019.19
      96 1020.58    96.2 1020.64   105.8 1023.82   115.6 1026.29   125.4 1026.75
   134.8 1026.56   144.1 1026.41   153.5 1026.31   162.9 1026.34   172.3 1027.48
   181.6 1029.99     191 1033.32   200.4 1036.95   209.7 1040.67
#Mann= 3 , 0 , 0
       0     .06       0    76.2    .045       0    96.2     .06       0
Bank Sta=76.2,96.2
XS Rating Curve= 0 ,0
Exp/Cntr=0.3,0.1

Type RM Length L Ch R = 1 ,9797.2  ,195.8,202.9,210.1
XS GIS Cut Line= 4
     1705438.057      192962.254     1705472.478      193014.478
     1705542.505       193090.44      1705617.28      193187.766
#Sta/Elev= 25
     8.9 1047.39    26.8 1040.61    35.7 1037.73    44.7 1036.14    53.6 1035.01
    62.5 1033.36    71.9 1029.23    81.3 1024.36    90.1  1020.4    90.7 1020.13
   100.1 1018.83   109.5 1019.34   110.1 1019.44   118.9 1020.85   128.3 1022.12
   137.7  1022.8   156.5 1023.32   194.2 1023.92   231.9 1024.95   241.4 1025.39
   250.8 1026.31   260.3  1028.3   269.7 1031.53   279.2 1035.25   288.6 1039.17
#Mann= 3 , 0 , 0
       0     .06       0    90.1    .045       0   110.1     .06       0
Bank Sta=90.1,110.1
XS Rating Curve= 0 ,0
Exp/Cntr=0.3,0.1

Type RM Length L Ch R = 1 ,9594.3  ,255.3,259.5,263.8
XS GIS Cut Line= 4
     1705236.284      192995.487     1705307.498      193108.243
     1705345.479      193200.822      1705483.16       193277.97
#Sta/Elev= 30
     9.5 1063.15    19.1 1059.21    38.1 1051.05    57.2 1042.19    66.7 1038.03
    76.2 1035.41    85.7 1033.82    95.3 1032.03   104.8 1028.59   114.3 1025.42
   123.8 1023.36   133.4  1022.2   143.4 1020.65   163.4 1016.17   173.4 1015.24
   183.4 1016.24   193.4 1018.29   203.4 1020.03   213.4  1021.1   223.4 1021.98
   243.3 1024.45   253.2 1026.53     263 1028.96   272.9 1031.59   292.6 1037.14
   322.2 1046.22   332.1 1049.42   341.9 1052.83   351.8 1056.41   391.3 1071.16
#Mann= 3 , 0 , 0
       0     .06       0   163.4    .045       0   183.4     .06       0
Bank Sta=163.4,183.4
XS Rating Curve= 0 ,0
Exp/Cntr=0.3,0.1

Type RM Length L Ch R = 1 ,9334.8  ,168.8,170.8,172.8
XS GIS Cut Line= 4
      1705065.37      193091.627     1705066.557      193147.411
     1705080.799       193228.12     1705172.191      193311.204
#Sta/Elev= 30
     9.3 1038.95    18.6 1035.15    27.9 1032.03    37.2 1029.92    46.5 1028.08
    55.8 1024.97    64.9 1020.17    73.1 1015.89      74 1015.42    83.1 1013.34
    92.2 1013.58    93.1 1013.71   101.3 1014.87   110.4 1016.23   119.5 1017.28
   128.6 1018.11   137.8 1018.93   147.3 1019.62   156.8 1020.31   166.3 1021.03
   175.8 1021.74   185.3 1022.46   194.8 1023.25   204.3 1024.12   213.8 1025.05
   223.3 1025.98   232.8 1026.92   242.3 1027.93   251.8 1028.91   261.3    1031
#Mann= 3 , 0 , 0
       0     .06       0    73.1    .045       0    93.1     .06       0
Bank Sta=73.1,93.1
XS Rating Curve= 0 ,0
Exp/Cntr=0.3,0.1

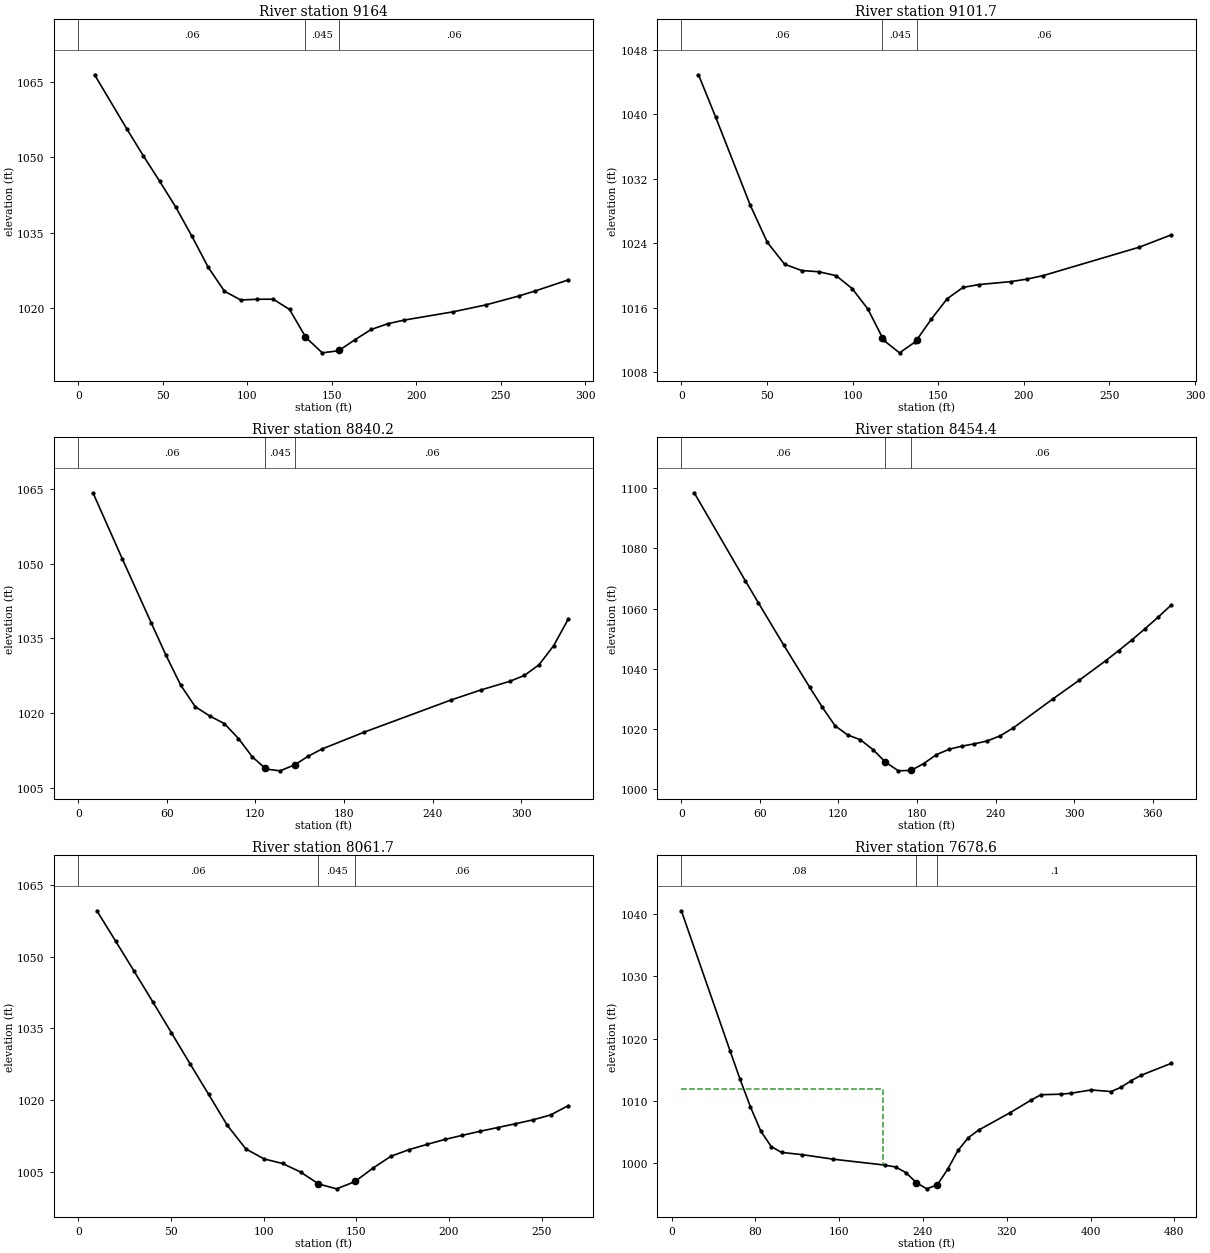
Type RM Length L Ch R = 1 ,9164    ,53.1,62.2,71.4
XS GIS Cut Line= 4
     1704893.269      193051.272      1704900.39      193166.402
     1704906.325       193243.55     1704939.558      193334.942
#Sta/Elev= 26
     9.6  1066.4    28.8 1055.58    38.4 1050.32    48.1 1045.24    57.7 1040.06
    67.3 1034.25    76.9 1028.11    86.5 1023.37    96.1 1021.63   105.7 1021.77
   115.3 1021.79     125 1019.75   134.4 1014.33   134.7 1014.16   144.4 1011.12
     154 1011.53   154.4 1011.62   163.7 1013.72   173.4 1015.77   183.1  1016.9
   192.7 1017.62   221.9 1019.28   241.3 1020.66   260.8 1022.43   270.5 1023.43
     290 1025.62
#Mann= 3 , 0 , 0
       0     .06       0   134.4    .045       0   154.4     .06       0
Bank Sta=134.4,154.4
XS Rating Curve= 0 ,0
Exp/Cntr=0.3,0.1

Type RM Length L Ch R = 1 ,9101.7  ,254.6,261.5,268.3
XS GIS Cut Line= 4
      1704850.54      193070.262     1704856.475      193160.467
     1704829.176      193229.307     1704771.018      193336.129
#Sta/Elev= 24
      10 1044.92    20.1 1039.63    40.2 1028.75    50.2 1024.13    60.3 1021.41
    70.3 1020.63    80.4 1020.48    90.4 1019.99    99.7  1018.4   108.9 1015.86
   117.4 1012.31   118.2 1011.97   127.4 1010.42   136.7  1011.8   137.4 1012.01
   145.9 1014.58   155.2 1017.13   164.5 1018.54   173.8 1018.89   192.5 1019.26
   201.9 1019.57   211.2    1020   267.4 1023.53   286.1 1025.06
#Mann= 3 , 0 , 0
       0     .06       0   117.4    .045       0   137.4     .06       0
Bank Sta=117.4,137.4
XS Rating Curve= 0 ,0
Exp/Cntr=0.3,0.1

Type RM Length L Ch R = 1 ,8840.2  ,377.4,385.8,394.2
XS GIS Cut Line= 4
     1704718.794      192961.067     1704649.953      193032.281
     1704588.234      193103.496      1704563.31       193239.99
#Sta/Elev= 24
     9.9 1064.23    29.7 1051.02    49.5 1038.04    59.4 1031.61    69.3 1025.64
    79.2 1021.29    89.1 1019.41      99 1017.88   108.5  1014.9   117.9 1011.21
   126.7 1008.91   127.3 1008.76   136.7 1008.41   146.7 1009.63   155.6 1011.32
     165 1012.78   193.3 1016.13   252.8 1022.66   272.6 1024.63   292.4 1026.38
   302.3 1027.57   312.2 1029.71   322.1 1033.54     332 1038.88
#Mann= 3 , 0 , 0
       0     .06       0   126.7    .045       0   146.7     .06       0
Bank Sta=126.7,146.7
XS Rating Curve= 0 ,0
Exp/Cntr=0.3,0.1

Type RM Length L Ch R = 1 ,8454.4  ,397.1,392.8,388.4
XS GIS Cut Line= 4
     1704547.138      192679.029       1704441.8      192730.956
     1704336.462      192779.916     1704232.608      192874.868
#Sta/Elev= 30
     9.8 1098.55    48.9 1069.22    58.7 1061.98    78.3 1047.75    97.9 1033.86
   107.7  1027.1   117.4 1020.95   127.1 1017.87   136.8 1016.28   146.5 1012.97
   155.8 1008.87   165.8 1005.93   175.5 1006.08   175.8 1006.15   185.2 1008.37
   194.9 1011.33   204.6 1013.12   214.2 1014.15   223.9 1014.92   233.6 1015.88
   243.7 1017.62   253.7 1020.27   283.9  1029.9     304 1036.13   324.1 1042.58
   334.1 1045.98   344.2 1049.54   354.2 1053.25   364.3 1057.15   374.3 1061.18
#Mann= 3 , 0 , 0
       0     .06       0   155.8    .045       0   175.8     .06       0
Bank Sta=155.8,175.8
XS Rating Curve= 0 ,0
Exp/Cntr=0.3,0.1

Type RM Length L Ch R = 1 ,8061.7  ,373.7,383.1,392.5
XS GIS Cut Line= 4
     1704296.405      192349.664     1704213.321      192406.041
     1704143.591      192459.452     1704102.049      192523.248
#Sta/Elev= 29
      10 1059.63    20.1 1053.29    30.1 1046.97    40.2 1040.55    50.2 1034.11
    60.2 1027.65    70.3  1021.2    80.3 1014.76    90.4 1009.77   100.4 1007.66
   110.2 1006.73   119.9 1004.94   129.4 1002.51   129.7 1002.43   139.4 1001.42
   149.2 1002.92   149.4 1002.98     159 1005.76   168.7 1008.24   178.5 1009.63
   188.2 1010.73   197.8 1011.76   207.3 1012.63   216.8 1013.47   226.3 1014.25
   235.8 1015.04   245.3 1015.86   254.9 1016.89   264.4 1018.85
#Mann= 3 , 0 , 0
       0     .06       0   129.4    .045       0   149.4     .06       0
Bank Sta=129.4,149.4
XS Rating Curve= 0 ,0
Exp/Cntr=0.3,0.1

Type RM Length L Ch R = 1 ,7678.6  ,436.3,443.7,451.1
XS GIS Cut Line= 4
     1704248.526      192061.562     1704183.185      192063.484
     1703900.679      192115.372     1703898.792      192239.875
#Sta/Elev= 30
     9.3 1040.51      56 1017.95    65.4 1013.47    75.3 1009.04    85.2 1005.16
    95.1  1002.7     105 1001.76   124.8  1001.4   154.5 1000.67     204  999.72
   213.9  999.42   223.8  998.51   233.7   996.9   243.7  995.92   253.7  996.57
   263.5  999.04   273.4 1002.07   283.3 1004.13   293.2 1005.35   322.9  1008.1
   342.7  1010.1   352.6 1011.01   371.8  1011.1   381.3 1011.25   400.5 1011.78
   419.6 1011.52   429.2 1012.21   438.8 1013.26   448.4 1014.14   477.1 1016.05
#Mann= 3 , 0 , 0
     9.3     .08       0   233.7    .045       0   253.7      .1       0
#XS Ineff= 2 , 0
           202.3 1011.88
Permanent Ineff=
       F       F
Bank Sta=233.7,253.7
XS Rating Curve= 0 ,0
Exp/Cntr=0.3,0.1

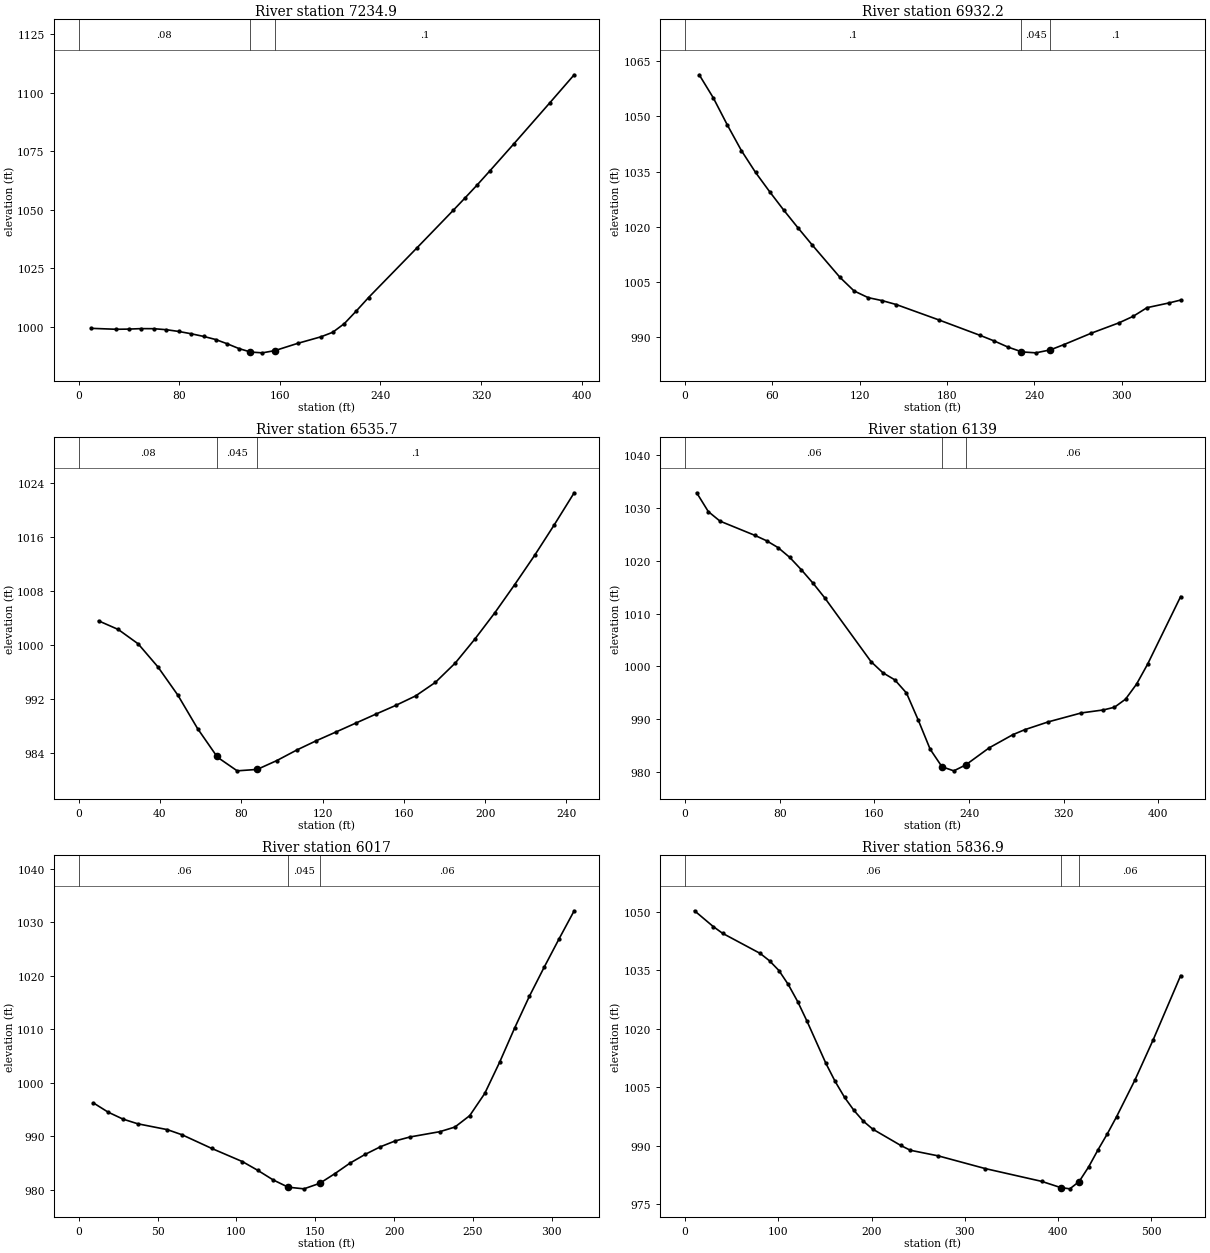
Type RM Length L Ch R = 1 ,7234.9  ,311.8,302.6,293.5
XS GIS Cut Line= 4
     1704199.969      191696.797     1704100.565      191690.862
     1703990.777      191670.091     1703808.291      191677.509
#Sta/Elev= 30
      10  999.24    29.9  998.84    39.8  998.92    49.8  999.12    59.7  999.09
    69.7  998.66    79.7   997.9    89.6  996.91    99.6  995.76   108.9  994.47
   118.2  992.63   127.5  990.59   136.1  989.21   136.8   989.1   146.1  988.77
   156.1  989.73   174.1  992.81   192.7  995.63     202  997.55   211.3 1001.28
   220.9 1006.73   230.5  1012.4     269 1033.64   297.8 1049.65   307.4 1055.07
   317.1 1060.65   326.7 1066.38   345.9 1078.01   374.7 1095.67     394 1107.61
#Mann= 3 , 0 , 0
       0     .08       0   136.1    .045       0   156.1      .1       0
Bank Sta=136.1,156.1
XS Rating Curve= 0 ,0
Exp/Cntr=0.3,0.1

Type RM Length L Ch R = 1 ,6932.2  ,402.1,396.5,390.9
XS GIS Cut Line= 4
     1704312.725      191327.443     1704143.591      191368.985
     1704005.613      191407.559     1703999.679      191429.813
#Sta/Elev= 29
     9.7 1061.35    19.4 1055.06      29 1047.71    38.7 1040.72    48.4 1034.79
    58.1 1029.54    67.7 1024.57    77.4 1019.79    87.1 1015.16   106.4 1006.24
   116.1 1002.54   125.8 1000.72   135.5   999.9   145.1  998.84   174.2  994.68
   202.8  990.44   212.4  988.93   221.9  987.26     231  986.02   231.5  985.95
     241   985.7     251  986.51   260.1  987.91   279.2  991.06   298.3  993.89
   307.9  995.64   317.4  997.99   332.8   999.3   340.5 1000.06
#Mann= 3 , 0 , 0
       0      .1       0     231    .045       0     251      .1       0
Bank Sta=231,251
XS Rating Curve= 0 ,0
Exp/Cntr=0.3,0.1

Type RM Length L Ch R = 1 ,6535.7  ,407.6,396.7,385.9
XS GIS Cut Line= 2
     1704029.351      190968.405     1703821.643      191095.997
#Sta/Elev= 27
     9.8 1003.64    19.5 1002.36    29.3 1000.23      39  996.82    48.8  992.64
    58.5  987.69      68  983.57    68.3  983.44      78  981.42    87.8  981.63
      88  981.65    97.5  982.94   107.3   984.5     117  985.89   126.8   987.2
   136.5  988.51   146.3  989.83     156  991.11   165.8  992.52   175.5  994.52
   185.3  997.39     195 1000.96   204.8 1004.85   214.5 1008.99   224.3 1013.32
     234 1017.86   243.8 1022.61
#Mann= 3 , 0 , 0
       0     .08       0      68    .045       0      88      .1       0
Bank Sta=68,88
XS Rating Curve= 0 ,0
Exp/Cntr=0.3,0.1

Type RM Length L Ch R = 1 ,6139    ,128.4,122,115.5
XS GIS Cut Line= 4
     1703837.382      190531.229      1703736.08      190651.417
     1703665.685      190783.624     1703672.553      190895.227
#Sta/Elev= 30
     9.8 1032.87    19.6 1029.31    29.5  1027.5    58.9 1024.81    68.8 1023.79
    78.6 1022.48    88.4 1020.64    98.2  1018.3   108.1 1015.75   117.9    1013
   157.2 1000.87   167.2  998.77   177.2  997.44   187.1  994.94   197.1  989.79
   207.1   984.3   217.1  980.97   227.1   980.2   237.1  981.31     257  984.56
     277  987.05     287  987.99     307  989.48   334.9  991.17   353.6  991.74
   362.9  992.25   372.2  993.77   381.5  996.61   390.8 1000.37   418.8 1013.21
#Mann= 3 , 0 , 0
       0     .06       0   217.1    .045       0   237.1     .06       0
Bank Sta=217.1,237.1
XS Rating Curve= 0 ,0
Exp/Cntr=0.3,0.1

Type RM Length L Ch R = 1 ,6017    ,168.6,180.1,191.6
XS GIS Cut Line= 4
        1703636.      190551.002     1703597.312      190625.883
     1703581.087       190721.98     1703577.343       190854.27
#Sta/Elev= 29
     9.4  996.22    18.7   994.5    28.1   993.2    37.5  992.32    56.2  991.23
    65.6  990.26    84.3  987.72   103.8  985.25   113.5  983.62   123.3  981.82
   132.8  980.46   142.8  980.15   152.8  981.18   162.3  982.97     172  984.96
   181.7  986.61   191.2  988.01   200.6  989.11   210.1  989.86     229  990.85
   238.5  991.71   247.9  993.85   257.4  997.99   266.8 1003.81   276.3  1010.2
   285.7 1016.18   295.2 1021.69   304.6 1026.97   314.1 1032.18
#Mann= 3 , 0 , 0
       0     .06       0   132.8    .045       0   152.8     .06       0
Bank Sta=132.8,152.8
XS Rating Curve= 0 ,0
Exp/Cntr=0.3,0.1

Type RM Length L Ch R = 1 ,5836.9  ,248.5,259.3,269.7
XS GIS Cut Line= 4
     1703662.727       190320.67     1703477.295      190571.347
     1703382.861      190676.082     1703369.125      190753.346
#Sta/Elev= 30
    10.1 1050.34    30.2 1046.28    40.2 1044.55    80.5 1039.38    90.5 1037.49
   100.6 1034.99   110.6  1031.4   120.7 1027.01   130.8 1021.92   150.9 1011.16
   160.9 1006.48     171 1002.38   181.1  999.03   191.1  996.28   201.2  994.23
   231.3  990.03   241.4  988.81   271.6  987.35   321.9  984.09   382.3  980.81
   402.5  979.23   412.5  978.89   422.5  980.77   432.7  984.54   442.8  988.96
   452.8  993.07   462.6  997.42   482.3 1006.85   501.9 1017.21   531.3 1033.68
#Mann= 3 , 0 , 0
       0     .06       0   402.5    .045       0   422.5     .06       0
Bank Sta=402.5,422.5
XS Rating Curve= 0 ,0
Exp/Cntr=0.3,0.1

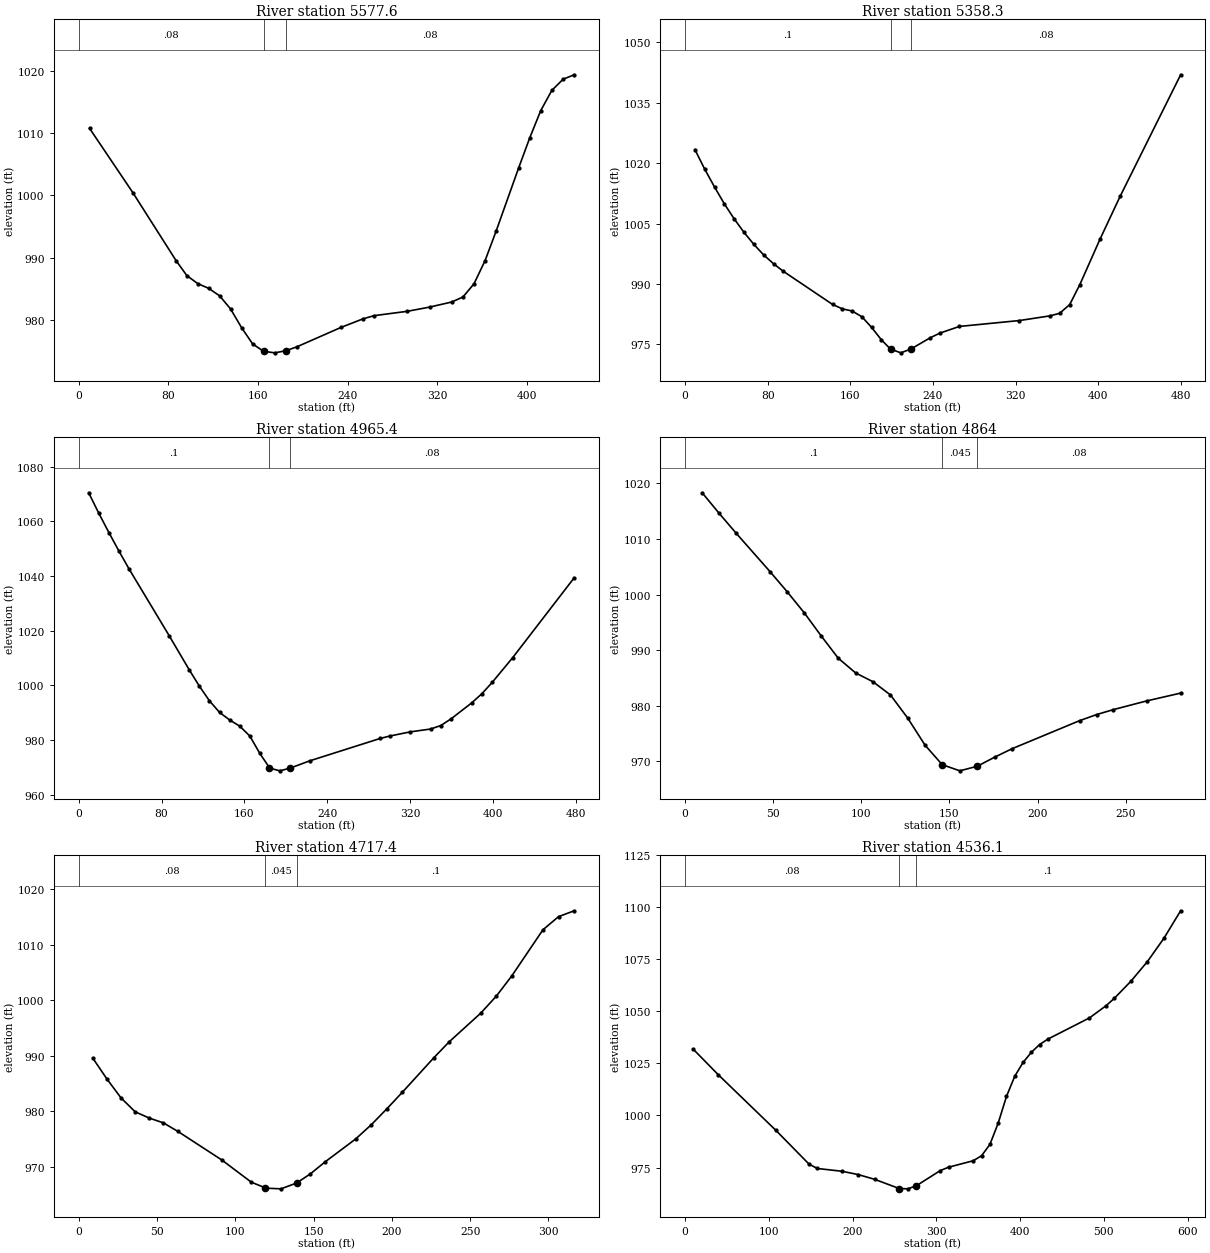
Type RM Length L Ch R = 1 ,5577.6  ,234.5,219.3,204.4
XS GIS Cut Line= 4
     1703458.408      190351.575     1703369.125      190425.405
     1703209.447      190475.197      1703151.07      190622.856
#Sta/Elev= 30
     9.7 1010.83    48.3 1000.47    86.9   989.5    96.5  987.09   106.2   985.8
   115.9  985.04   125.7  983.83   135.5  981.71   145.4  978.67   155.2  976.07
   164.9  974.89   174.9  974.64   184.9  974.98   194.6  975.61   233.9  978.73
   253.6  980.12   263.4  980.63     293  981.33   312.9  982.01   332.7  982.83
   342.7  983.64   352.6  985.77   362.5  989.52   372.4  994.31   392.3  1004.4
   402.2 1009.25   412.1 1013.68     422 1016.94     432 1018.73   441.9 1019.45
#Mann= 3 , 0 , 0
       0     .08       0   164.9    .045       0   184.9     .08       0
Bank Sta=164.9,184.9
XS Rating Curve= 0 ,0
Exp/Cntr=0.3,0.1

Type RM Length L Ch R = 1 ,5358.3  ,394.5,392.9,391.3
XS GIS Cut Line= 4
     1703257.522      190142.105     1703181.976      190274.311
     1703116.731      190389.348     1703020.581      190559.328
#Sta/Elev= 30
     9.5  1023.4      19 1018.53    28.6 1014.05    38.1 1009.87    47.6 1006.16
    57.1 1002.81    66.6  999.84    76.1  997.22    85.7  995.02    95.2  993.14
   142.8  984.92   152.3  983.82   161.7   983.3   171.2  981.86   180.6  979.22
   190.1  976.12   198.9  973.83   208.9   972.9   218.9  973.88   237.3  976.64
   246.7   977.8   265.6  979.46   323.6  980.92   352.9  982.07   362.6  982.71
   372.4  984.89   382.2  989.85   401.7 1001.12   421.2 1011.78   479.8 1041.98
#Mann= 3 , 0 , 0
       0      .1       0   198.9    .045       0   218.9     .08       0
Bank Sta=198.9,218.9
XS Rating Curve= 0 ,0
Exp/Cntr=0.3,0.1

Type RM Length L Ch R = 1 ,4965.4  ,105.1,101.4,97.8
XS GIS Cut Line= 4
     1702907.261      189980.709      1702828.28      190114.633
      1702754.45      190272.594     1702726.979      190418.537
#Sta/Elev= 30
     9.7  1070.4    19.4 1062.96    29.2 1055.85    38.9 1049.08    48.6 1042.58
    87.5 1018.06   106.9 1005.56   116.6  999.64   126.3   994.3     136  990.08
   145.8  987.29   155.5  985.05   165.2  981.44   174.9  975.07   184.2  969.83
   184.5  969.67   194.2   968.7   204.2   969.7   223.3  972.39   291.1  980.55
   300.8  981.47   320.2  982.96   339.7  983.99   349.6  985.28   359.5  987.72
   379.3  993.53   389.2  996.89   399.1 1001.02   418.9 1010.07   478.3  1039.3
#Mann= 3 , 0 , 0
       0      .1       0   184.2    .045       0   204.2     .08       0
Bank Sta=184.2,204.2
XS Rating Curve= 0 ,0
Exp/Cntr=0.3,0.1

Type RM Length L Ch R = 1 ,4864    ,137.6,146.6,155.7
XS GIS Cut Line= 4
     1702749.907      189974.417     1702731.187      190059.282
      1702703.73      190164.116     1702723.698      190247.733
#Sta/Elev= 23
     9.7 1018.31    19.3 1014.62      29 1011.03    48.3 1004.09    57.9 1000.52
    67.6  996.73    77.2  992.58    86.9  988.56    96.8   985.9   106.6  984.33
   116.5  981.96   126.3   977.8   136.2   972.9   145.9  969.41   155.9   968.3
   165.9  969.14   175.6  970.75   185.4  972.26   223.9  977.33   233.5  978.42
     243  979.31   262.1  980.89   281.2  982.28
#Mann= 3 , 0 , 0
       0      .1       0   145.9    .045       0   165.9     .08       0
Bank Sta=145.9,165.9
XS Rating Curve= 0 ,0
Exp/Cntr=0.3,0.1

Type RM Length L Ch R = 1 ,4717.4  ,176.9,181.3,185.7
XS GIS Cut Line= 4
     1702662.546      189965.681     1702623.857      190015.601
     1702557.712      190095.475      1702540.24      190243.989
#Sta/Elev= 27
       9  989.57      18  985.82    27.1  982.38    36.1  979.89    45.1  978.76
    54.1   977.9    63.2  976.39    91.4  971.22   110.3  967.21   119.2   966.2
   119.7  966.14   129.2  966.02   139.2  967.07     148  968.72   157.4  970.88
   176.8  974.98   186.8  977.54   196.8  980.43   206.7  983.41   226.7  989.59
   236.6  992.49   256.6  997.61   266.6 1000.68   276.5 1004.33   296.5 1012.67
   306.4 1015.02   316.4 1016.08
#Mann= 3 , 0 , 0
       0     .08       0   119.2    .045       0   139.2      .1       0
Bank Sta=119.2,139.2
XS Rating Curve= 0 ,0
Exp/Cntr=0.3,0.1

Type RM Length L Ch R = 1 ,4536.1  ,335.2,340.8,346.3
XS GIS Cut Line= 4
     1702673.538      189811.373     1702514.718      189890.783
     1702398.823      189980.924     1702182.055      190137.598
#Sta/Elev= 30
     9.9 1031.76    39.5 1019.62   108.5  992.82     148  976.63   157.8  974.54
   187.4  973.19   206.9  971.59   226.5   969.3   255.7   964.9   265.7  964.75
   275.7  966.11   304.8  973.53   314.6  975.13   344.2  978.26   354.1  980.67
     364  986.07   373.9   996.3   383.8 1009.13   393.7 1018.85   403.6 1025.45
   413.5 1030.34   423.4 1034.08   433.4 1036.72   482.9 1046.86   502.7 1052.71
   512.6 1056.26   532.4 1064.48   552.2 1073.96     572 1085.23   591.8 1098.33
#Mann= 3 , 0 , 0
       0     .08       0   255.7    .045       0   275.7      .1       0
Bank Sta=255.7,275.7
XS Rating Curve= 0 ,0
Exp/Cntr=0.3,0.1

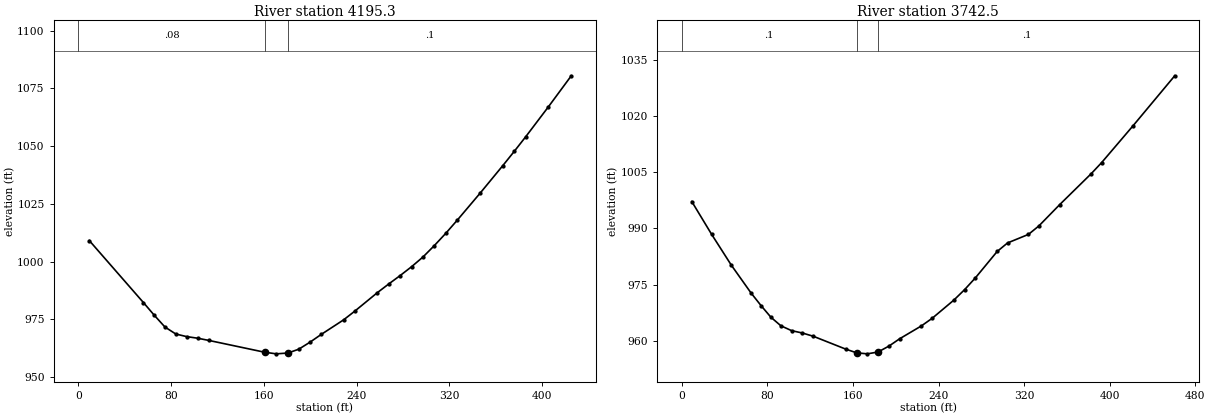
Type RM Length L Ch R = 1 ,4195.3  ,451.1,452.8,454.4
XS GIS Cut Line= 4
     1702448.186      189581.729     1702362.337      189618.214
     1702209.956      189680.455      1702083.33      189789.911
#Sta/Elev= 30
     9.3 1009.11      56  982.27    65.3  976.81    74.6  971.66      84  968.62
    93.3  967.51     103  966.79   112.6  965.84   160.7  960.73   170.7  960.04
   180.7  960.39   190.1  962.05   199.8  965.09   209.5  968.45   228.8  974.76
   238.5  978.55   257.9  986.53   267.7  990.28   277.6  993.94   287.4  997.75
   297.3 1001.98   307.1 1006.92     317 1012.25   326.8 1017.88   346.5 1029.56
   366.2 1041.56     376 1047.69   385.9 1054.02   405.6 1067.07   425.3 1080.47
#Mann= 3 , 0 , 0
       0     .08       0   160.7    .045       0   180.7      .1       0
Bank Sta=160.7,180.7
XS Rating Curve= 0 ,0
Exp/Cntr=0.3,0.1

Type RM Length L Ch R = 1 ,3742.5  ,562.3,549.6,536.9
XS GIS Cut Line= 4
     1702317.267      189163.217     1702231.418      189197.557
     1702038.259      189257.651      1701941.68      189392.862
#Sta/Elev= 30
     9.2   997.2    27.7  988.46    46.2  980.19    64.7  972.74      74  969.39
    83.2  966.29    92.5  964.01   102.6   962.7   112.7  962.07   122.8  961.21
   153.1  957.78   163.4  956.78   173.4  956.51   183.4     957   193.6  958.58
   203.7  960.55     224  963.98   234.1  966.02   254.3  970.86   264.4  973.67
   274.5  976.82   294.8  983.85   304.5  986.13   324.1  988.42   333.8  990.67
   353.4   996.4   382.7 1004.61   392.5 1007.59   421.8  1017.4   460.9 1030.79
#Mann= 3 , 0 , 0
       0      .1       0   163.4    .045       0   183.4      .1       0
Bank Sta=163.4,183.4
XS Rating Curve= 0 ,0
Exp/Cntr=0.3,0.1