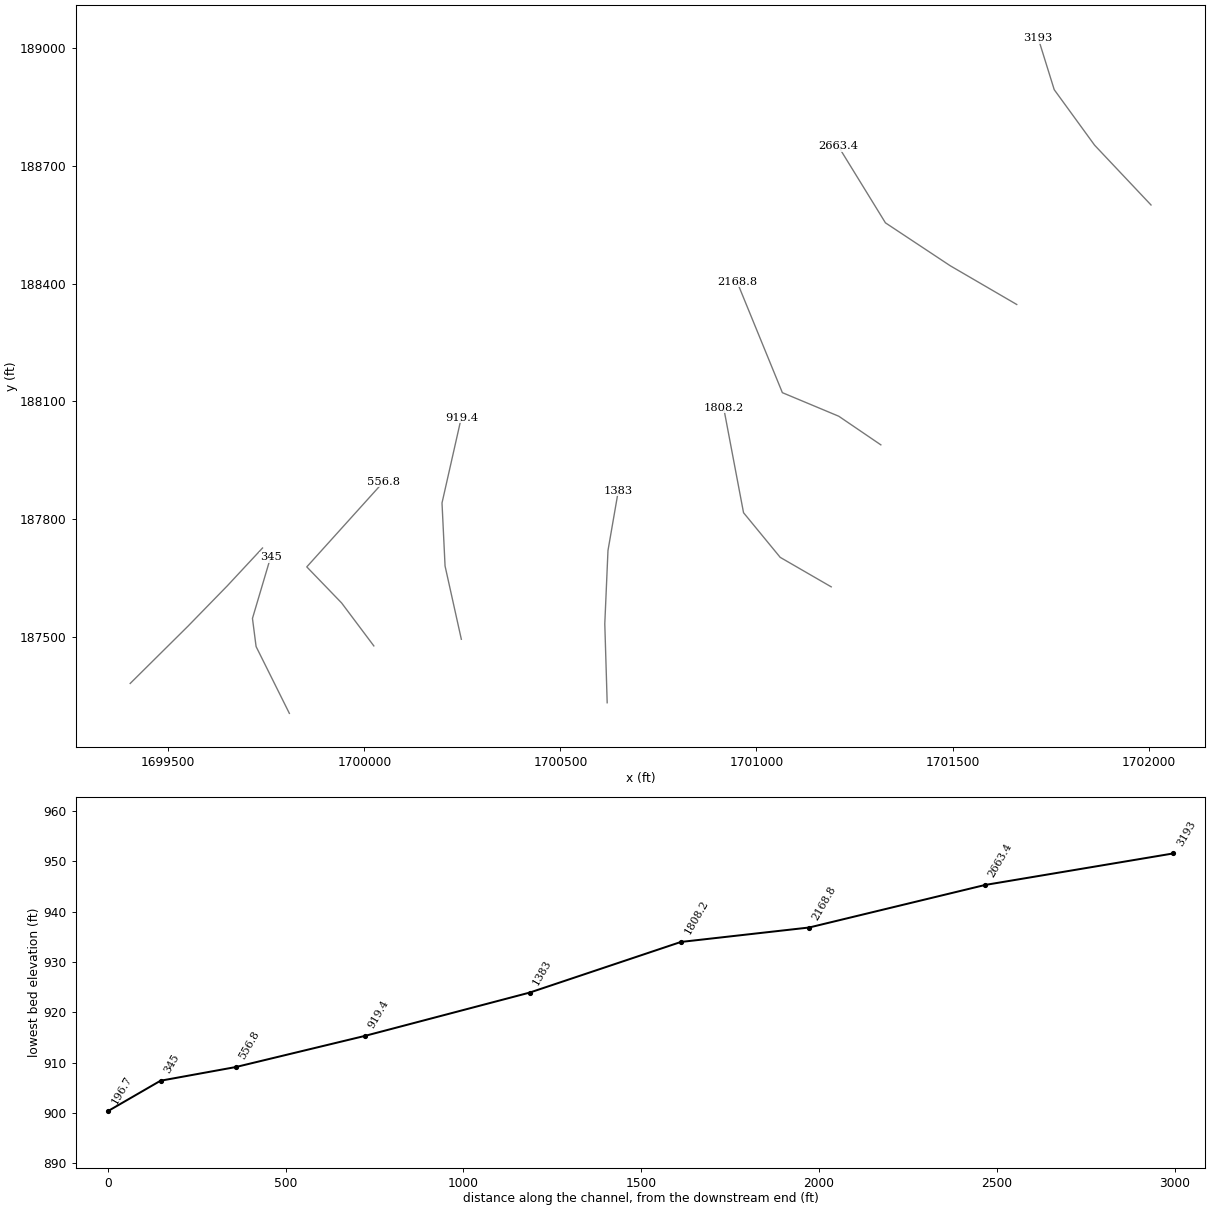
HEC-RAS study Sims Fork.prj: Sims Fork

--- Sims Fork.g01 (geometry) --- (continued)

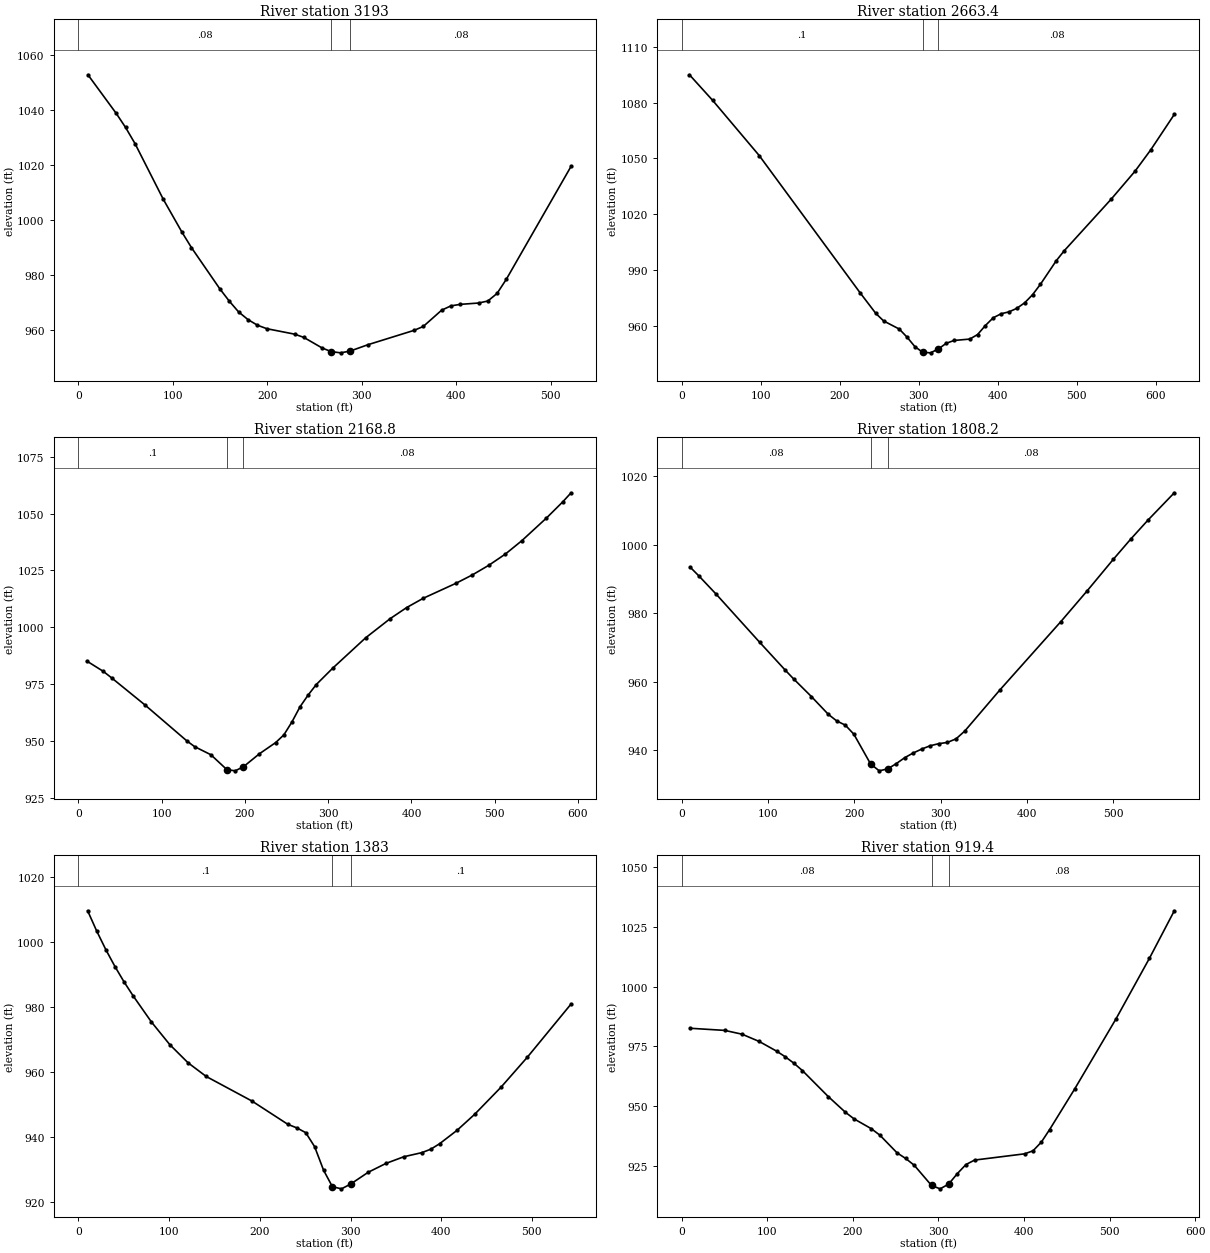
Type RM Length L Ch R = 1 ,3193    ,522.5,529.6,536.7
XS GIS Cut Line= 4
     1702006.066       188600.91      1701862.27      188753.291
     1701759.252      188894.941     1701718.474       189025.86
#Sta/Elev= 30
      10 1052.81    39.9 1038.79    49.9 1033.62    59.9 1027.74    89.8 1007.48
   109.7  995.44   119.7  989.85   149.7  974.87   159.6  970.44   169.6  966.45
   179.6  963.64   189.6  961.61   199.5  960.34     229  958.35   238.7  957.17
   258.2   953.3   267.6  952.01   277.6  951.55   287.6  952.18   306.8  954.53
   355.5  959.74   365.2  961.15   384.7  967.09   394.5  968.65   404.3   969.2
   423.8  969.69   433.6  970.42   443.4  973.18   453.2  978.34   521.8 1019.47
#Mann= 3 , 0 , 0
       0     .08       0   267.6    .045       0   287.6     .08       0
Bank Sta=267.6,287.6
XS Rating Curve= 0 ,0
Exp/Cntr=0.3,0.1

Type RM Length L Ch R = 1 ,2663.4  ,509.5,494.6,499.2
XS GIS Cut Line= 4
      1701663.67      188347.177     1701494.119      188445.903
     1701328.861       188555.36     1701208.673      188750.665
#Sta/Elev= 30
     9.8 1095.08    39.2 1081.28    98.1 1051.58   225.9  977.61   245.8   966.5
   255.7  962.46   275.5  958.08   285.4  953.69   295.3  948.59   305.1   945.6
   315.1  945.28   325.1  947.41     335  950.44   344.9  951.95   364.7  952.69
   374.6  955.13   384.5     960   394.4  964.16   404.4  966.33   414.4  967.36
   424.3  969.25   434.3  972.26   444.3  976.63   454.2  982.22   474.2  994.88
   484.2 1000.22     544 1028.18   573.9  1043.1   593.8 1054.59   623.7 1073.73
#Mann= 3 , 0 , 0
       0      .1       0   305.1    .045       0   325.1     .08       0
Bank Sta=305.1,325.1
XS Rating Curve= 0 ,0
Exp/Cntr=0.3,0.1

Type RM Length L Ch R = 1 ,2168.8  ,370.4,360.6,350.8
XS GIS Cut Line= 4
     1701317.132      187989.239     1701209.821       188062.21
     1701066.025      188122.304      1700950.13      188405.604
#Sta/Elev= 30
      10  985.15    29.9  980.58    39.9  977.72    79.9  965.81   129.8  950.12
   139.5  947.48     159  943.92   178.2  937.38   188.2  936.83   198.2  938.64
   217.4  944.36   236.9  949.28   246.7  952.65   256.4  958.34   266.1  965.01
   275.9  970.21   285.6  974.79   305.4  982.02   344.9  995.36   374.5 1003.83
   394.2 1008.69     414 1012.75   453.5 1019.38   473.2 1023.07     493 1027.32
   512.7 1032.21   532.5  1038.1   562.1 1048.08   581.8 1055.24   591.7  1059.2
#Mann= 3 , 0 , 0
       0      .1       0   178.2    .045       0   198.2     .08       0
Bank Sta=178.2,198.2
XS Rating Curve= 0 ,0
Exp/Cntr=0.3,0.1

Type RM Length L Ch R = 1 ,1808.2  ,439.9,425.2,410.6
XS GIS Cut Line= 4
     1701190.586       187627.15       1701060.5      187702.356
        1700967.      187816.181     1700916.185      188084.485
#Sta/Elev= 30
      10  993.42      20  990.89    40.1  985.53    90.2  971.55   120.2  963.31
   130.2  960.68   150.3  955.65   169.9  950.45   179.7  948.52   189.5  947.32
   199.4  944.67   218.8  935.97   228.8  933.96   238.8  934.56   248.5  936.06
   258.3   937.8   268.1  939.17   277.9  940.31   287.7  941.28   297.6  941.89
   307.7  942.26   317.8  943.31   327.9  945.59   368.4  957.55   439.2  977.57
   469.5  986.51   499.8  995.72   520.1 1001.67   540.3 1007.28   570.6 1015.21
#Mann= 3 , 0 , 0
       0     .08       0   218.8    .045       0   238.8     .08       0
Bank Sta=218.8,238.8
XS Rating Curve= 0 ,0
Exp/Cntr=0.3,0.1

Type RM Length L Ch R = 1 ,1383    ,461.8,463.6,465.3
XS GIS Cut Line= 4
     1700619.288       187331.56      1700613.19      187532.787
     1700621.321      187719.786     1700647.744      187872.231
#Sta/Elev= 30
    10.1 1009.48    20.1 1003.24    30.2  997.49    40.3  992.28    50.3  987.57
    60.4  983.24    80.5  975.23   100.7  968.28   120.8   962.7   140.9  958.48
   191.3  950.92   230.9  943.75   240.7  942.67   250.6  941.19   260.4  936.88
   270.3  929.61     280  924.56     290   923.9     300  925.35   319.5     929
   339.2  931.74   358.9  933.79   378.6  935.04   388.5   936.1   398.2  937.78
   417.5  941.92   436.8  946.82   465.9  955.17   494.9  964.39   543.2  980.79
#Mann= 3 , 0 , 0
       0      .1       0     280    .045       0     300      .1       0
Bank Sta=280,300
XS Rating Curve= 0 ,0
Exp/Cntr=0.3,0.1

Type RM Length L Ch R = 1 ,919.4   ,348.1,362.6,377.1
XS GIS Cut Line= 4
     1700247.382      187493.489     1700205.881      187680.246
     1700198.099      187841.065     1700247.382      188058.948
#Sta/Elev= 30
    10.1  982.55    50.3  981.66    70.5  980.07    90.6  977.02   110.8  972.99
   120.8  970.66   130.9  967.97     141  964.85   171.2  953.97   191.3  947.37
   201.4   944.6   221.5   940.5   231.6  937.77   251.7  930.36   261.8     928
   271.8  925.15     292  916.69     302  915.29     312  917.29   322.1  921.66
   332.2  925.47   342.3  927.34   400.9  929.96   410.6  931.23   420.3  934.86
     430  940.13   459.2  957.09   507.7  986.58   546.6 1011.85   575.7 1031.77
#Mann= 3 , 0 , 0
       0     .08       0     292    .045       0     312     .08       0
Bank Sta=292,312
XS Rating Curve= 0 ,0
Exp/Cntr=0.3,0.1

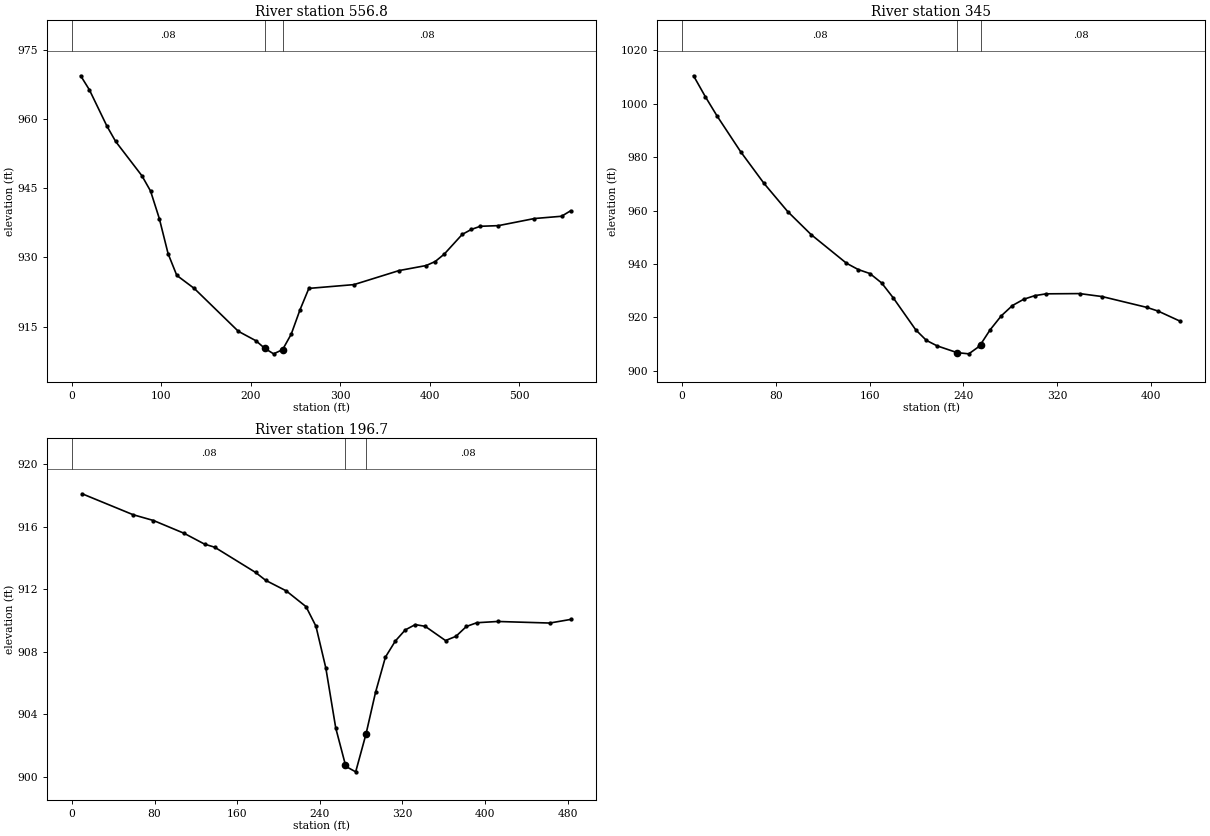
Type RM Length L Ch R = 1 ,556.8   ,225.1,211.7,198.4
XS GIS Cut Line= 4
     1700024.237      187476.555     1699942.163      187585.988
     1699853.255      187678.062     1700049.194      187895.217
#Sta/Elev= 30
     9.8  969.32    19.5  966.29    39.1  958.43    48.9  955.09    78.2  947.68
    87.9  944.36    97.7  938.39   107.5  930.79   117.2   926.1   136.8  923.26
     186  913.99   205.7  911.94   215.4  910.32   225.4  909.11   235.4  910.01
   245.1  913.37   254.9  918.64   264.8  923.28   315.2   924.1   365.6  927.14
   395.9  928.23     406   929.1   416.1   930.7   436.2  934.97   446.3  936.04
   456.4  936.73   476.6  936.87   516.9  938.41   547.2   938.9   557.3  940.08
#Mann= 3 , 0 , 0
       0     .08       0   215.4    .045       0   235.4     .08       0
Bank Sta=215.4,235.4
XS Rating Curve= 0 ,0
Exp/Cntr=0.3,0.1

Type RM Length L Ch R = 1 ,345     ,166.3,148.3,130.3
XS GIS Cut Line= 4
     1699808.861      187304.501     1699723.997      187474.886
     1699714.747      187546.661     1699760.914      187702.261
#Sta/Elev= 30
      10 1010.42      20 1002.63    30.1  995.34    50.1  982.04    70.1  970.13
    90.2  959.64   110.2  951.01   140.3   940.3   150.3  937.94   160.3  936.43
   170.3  932.92   180.3  927.28   199.4  915.35   208.4  911.44   217.5  909.39
   234.6  906.84   244.6  906.39   253.7  909.26   254.6  909.87   262.7  915.34
   272.3  920.62   281.8  924.47   291.4  926.81   300.9  928.17   310.5  928.84
   339.1  928.93   358.2  927.82   396.4  923.76   405.9  922.39     425  918.54
#Mann= 3 , 0 , 0
       0     .08       0   234.6    .045       0   254.6     .08       0
Bank Sta=234.6,254.6
XS Rating Curve= 0 ,0
Exp/Cntr=0.3,0.1

Type RM Length L Ch R = 1 ,196.7   ,195.2,196.7,198.3
XS GIS Cut Line= 4
     1699402.962      187380.813     1699550.322      187526.857
     1699650.975      187630.141     1699740.396      187726.199
#Sta/Elev= 30
     9.9  918.12    59.3  916.78      79  916.41   108.7  915.59   128.4   914.9
   138.3   914.7   177.8  913.09   187.7  912.58   207.5  911.91   226.7   910.9
   236.3  909.65   245.9  906.97   255.5  903.13   264.8  900.79   265.2  900.68
   274.8  900.33   284.8  902.75     294  905.41   303.6  907.67   313.2   908.7
   322.8  909.41   332.5  909.75   342.1  909.64   361.8  908.73   371.9     909
     382  909.63   392.1  909.87   412.3  909.95   462.7  909.85   482.9  910.08
#Mann= 3 , 0 , 0
       0     .08       0   264.8    .045       0   284.8     .08       0
Bank Sta=264.8,284.8
XS Rating Curve= 0 ,0
Exp/Cntr=0.3,0.1

Chan Stop Cuts=-1
Use User Specified Reach Order=0